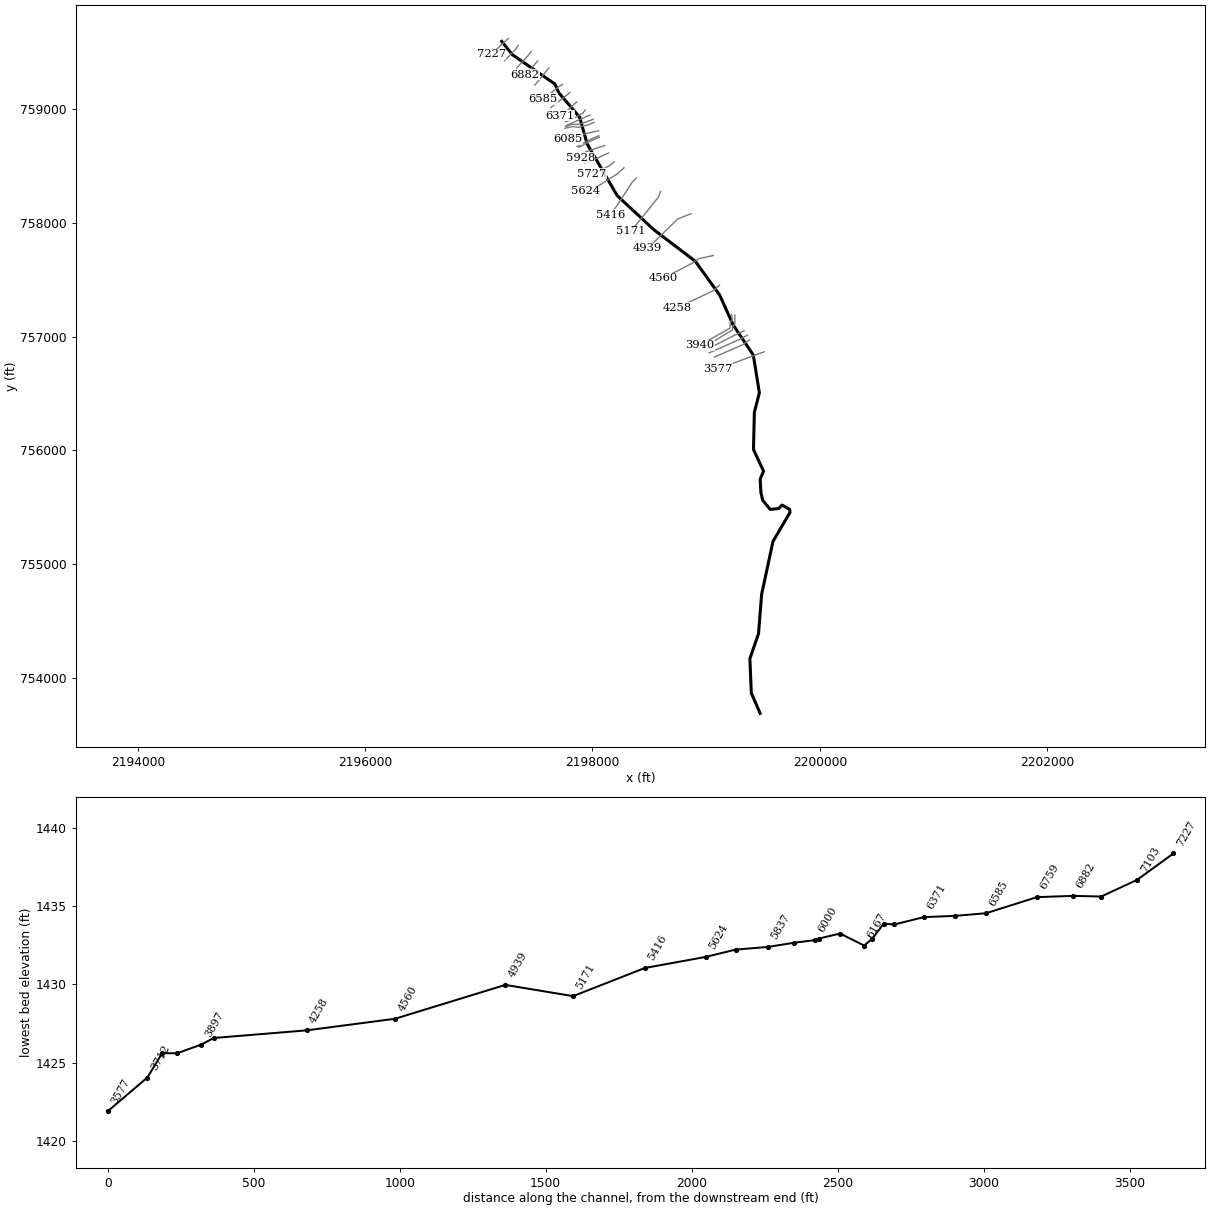
--- LIPECKSRN.prj (project) ---

Proj Title=LIPECKSRN
Current Plan=p01
Default Exp/Contr=0,0
English Units
Geom File=g01
Flow File=f01
Plan File=p01
BEGIN DESCRIPTION:
---------- MODELED AS PART OF WVEMD CTP PROGRAM, 2023----------
Stream Name: Little Pecks Run
Flood Zone:  AFH
Upshur County, WV
HEC-RAS Version: RAS 6.3
Vertical Datum: NAVD88
Projection: NAD 1983 StatePlane West Virginia S FIPS 4702 (US Feet)
Terrain: 1-meter LIDAR (FEMA Region III 3DEP collected 2016-2018)
Land Use: 2019 NLCD
Hydrologic Method:
WV SIR2010-5033 regression equations
Additional Model Notes:
None
END DESCRIPTION:
DSS Export Rating Curves= 0
DSS Export Rating Curve Sorted= 0
DSS Export Volume Flow Curves= 0
DXF OffsetX= 0
DXF OffsetY= 0
DXF ScaleX= 0
DXF ScaleY= 0

--- LIPECKSRN.p01 (plan) ---

Plan Title=Floodplain
Program Version=6.30
Short Identifier=Floodplain
Geom File=g01
Flow File=f01
Subcritical Flow
K Sum by GR= 0
Std Step Tol= 0.01
Critical Tol= 0.01
Num of Std Step Trials= 20
Max Error Tol= 0.3
Flow Tol Ratio= 0.001
Split Flow NTrial= 30
Split Flow Tol= 0.02
Split Flow Ratio= 0.02
Log Output Level= 0
Friction Slope Method= 1
Unsteady Friction Slope Method= 2
Unsteady Bridges Friction Slope Method= 1
Parabolic Critical Depth
Global Vel Dist= 0 , 0 , 0
Global Log Level= 0
CheckData=False
Encroach Param=-1 ,0,0, 0
Mapping Interval=1HOUR
Computation Time Step Use Courant=        0
Computation Time Step Use Time Series=    0
Computation Time Step Count To Double=0
Computation Time Step Max Doubling=0
Computation Time Step Max Halving=0
Computation Time Step Residence Courant=0
Run HTab= 0
Run UNet= 0
Run Sediment= 0
Run PostProcess= 0
Run WQNet= 0
Run RASMapper=-1
UNET Theta= 0
UNET Theta Warmup= 0
UNET ZTol= 0
UNET ZSATol= 0
UNET MxIter= 0
UNET Max Iter WO Improvement= 0
UNET MaxInSteps= 0
UNET DtIC= 0
UNET DtMin= 0
UNET MaxCRTS= 0
UNET WFStab= 0
UNET SFStab= 0
UNET WFX= 1
UNET SFX= 1
UNET Gravity=32.17405
UNET 1D Methodology=Finite Difference
UNET DSS MLevel= 1
UNET Pardiso=0
UNET DZMax Abort= 0
UNET Use Existing IB Tables= 0
UNET Froude Reduction=False
UNET Froude Limit= 0
UNET Froude Power= 0
UNET D1 Cores= 0
UNET WindReference=Eulerian
UNET WindDragFormulation=Hsu (1988)
UNET D2 Coriolis=0
UNET D2 Cores= 0
UNET D2 Theta= 1
UNET D2 Theta Warmup= 1
UNET D2 Z Tol= 0.01
UNET D2 Volume Tol= 0.01
UNET D2 Max Iterations= 20
UNET D2 Equation= 0
UNET D2 RampUpFraction=0.1
UNET D2 TimeSlices= 1
UNET D2 Turbulence Formulation=Non-Conservative (original)
UNET D2 Eddy Viscosity=0.3
UNET D2 Transverse Eddy Viscosity=0.1
UNET D2 Smagorinsky Mixing=0
UNET D2 BCVolumeCheck=0
UNET D2 Cores=0
UNET D2 SolverType=PARDISO (Direct)
UNET D2 Minimum Iterations= 3
UNET D2 Maximum Iterations= 30
UNET D2 Restart Number= 10
UNET D2 Relaxation Coeff=1.3
UNET D2 SOR Precondition Iterations= 10
UNET D2 ILUT Maximum Fill= 8
UNET D2 ILUT Tolerance=1E-08
UNET D2 Convergence Tolerance=0.00001
UNET D1D2 MaxIter= 0
UNET D1D2 ZTol=0.01
UNET D1D2 QTol=0.1
UNET D1D2 MinQTol=1
Write IC File= 0
Write IC File at Fixed DateTime=0
Write IC File at Sim End=0
Echo Input=False
Echo Parameters=False
Echo Output=False
Write Detailed= 0
HDF Write Warmup=0
HDF Write Time Slices=0
HDF Flush=0
HDF Compression= 1
HDF Chunk Size= 1
HDF Spatial Parts= 1
HDF Use Max Rows=0
HDF Fixed Rows= 1
Calibration Method= 0
Calibration Iterations= 20
Calibration Max Change=0.05
Calibration Tolerance=0.2
Calibration Maximum=1.5
Calibration Minimum=0.5
Calibration Optimization Method= 1
WQ AD Non Conservative
WQ ULTIMATE=-1
WQ Max Comp Step=1HOUR
WQ Output Interval=15MIN
WQ Output Selected Increments= 0
WQ Output face flow=0
WQ Output face velocity=0
WQ Output face area=0
WQ Output face dispersion=0
WQ Output cell volume=0
WQ Output cell surface area=0
WQ Output cell continuity=0
WQ Output cumulative cell continuity=0
WQ Output face conc=0
WQ Output face dconc_dx=0
WQ Output face courant=0
WQ Output face peclet=0
WQ Output face adv mass=0
WQ Output face disp mass=0
WQ Output cell mass=0
WQ Output cell source sink temp=0
WQ Output nsm pathways=0
WQ Output nsm derived pathways=0
WQ Create Restart=0
WQ Fixed Restart=0
WQ System Summary=0
WQ Write To DSS=0
Sorting and Armoring Iterations= 10
XS Update Threshold= 0.02
Bed Roughness Predictor= 0
Hydraulics Update Threshold= 0.02
Energy Slope Method= 1
Volume Change Method= 1
Sediment Retention Method= 0
Sediment TS Multiplier= 1
Warm Up Method= 0
XS Weighting Method= 0
Number of US Weighted Cross Sections= 1
Number of DS Weighted Cross Sections= 1
Upstream XS Weight=0
Main XS Weight=1
Downstream XS Weight=0
Number of DS XS's Weighted with US Boundary= 1
Upstream Boundary Weight= 1
Weight of XSs Associated with US Boundary= 0
Number of US XS's Weighted with DS Boundary= 1
Downstream Boundary Weight= 0.5
Weight of XSs Associated with DS Boundary= 0.5
Percentile Method= 0
Sediment Output Level= 3
Mass or Volume Output= 0
Output Increment Type= 1
Profile and TS Output Increment= 1
Transport Output Increment 1
XS Output Flag= 0
XS Output Increment= 10
Read HDF5 Sediment Hotstart= 0
Sediment Hotstart Type= 0
Write Gradation File= 0
Read Gradation Hotstart= 0
Write HDF5 File= 1
Write Binary Output= 1
Write DSS Sediment File= 0
DSS Sediment Output Type= 1
SV Curve= 0
Specific Gage Flag= 0
Subcell Erosion Methods= 0
Subcell Deposition Methods= 0
Advection Scheme= 1
Matrix Solver= 0
Implicit Weighting Factor= 1
Maximum Outer Loop Convergence Iterations= 5
Convergence Maximum Absolute= 0.001
Convergence RMSE= 0.0001
Grain Fractions Max Abs Error= 0.001
Max Subgrid Regions= 1
Max Subgrid Length Scale= 3.402823E+38
Initial Layer Thickness= 3.402823E+38
Min Layer Thickness= 3.402823E+38
Max Layer Thickness= 3.402823E+38
Number of Layers= 5

--- LIPECKSRN.f01 (steady flow) ---

Flow Title=Flows
Program Version=6.31
Number of Profiles= 1
Profile Names=01pct
River Rch & RM=LIPECKSRN,Main,7227
     311
River Rch & RM=LIPECKSRN,Main,6271
     356
River Rch & RM=LIPECKSRN,Main,4939
     396
River Rch & RM=LIPECKSRN,Main,3577
     478
Boundary for River Rch & Prof#=LIPECKSRN,Main            , 1
Up Type= 0
Dn Type= 3
Dn Slope=0.00615
DSS Import GetInterval= 0
DSS Import GetPeak= 0
DSS Import FillOption= 0

--- LIPECKSRN.g01 (geometry) ---

Geom Title=Geometry
Program Version=6.31

River Reach=LIPECKSRN       ,Main
Reach XY= 30
     2197201.053      759598.746     2197294.629      759482.334
      2197668.96        759224.1     2197703.528      759146.721
     2197887.217      758931.412     2197953.063      758696.099
     2198217.937      758240.669      2198541.33      757940.169
     2198903.728      757665.165     2199119.696      757365.809
     2199236.651      757105.829     2199415.447      756837.951
     2199468.644      756506.316     2199424.518      756335.133
      2199416.82      756007.103     2199505.445      755816.403
     2199475.713      755746.265     2199482.151      755627.278
     2199498.234      755559.514     2199564.109      755480.132
      2199638.74      755487.744     2199667.357      755518.049
     2199735.292      755480.733     2199738.268      755453.862
     2199588.347      755197.774      2199488.39        754732.3
     2199460.975      754385.412     2199385.085      754166.812
     2199397.647      753864.623     2199475.312      753684.912

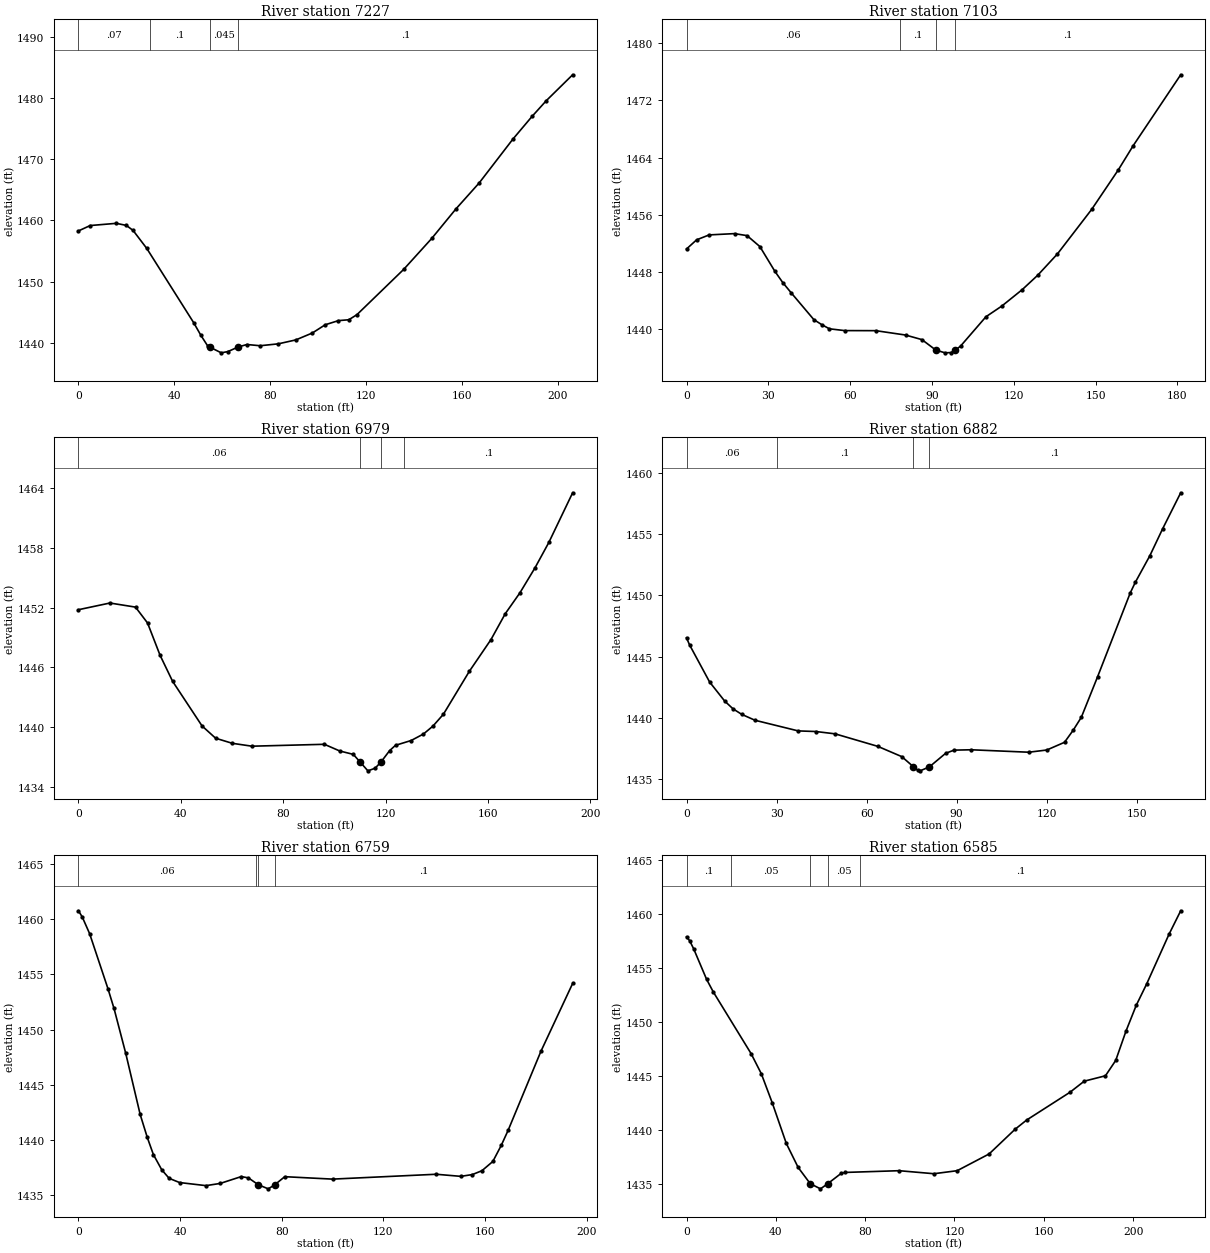
Type RM Length L Ch R = 1 ,7227    ,124.1,124.1,124.1
XS GIS Cut Line= 2
2197259.75611442759625.8374206682197108.45153322759485.708746027
#Sta/Elev= 30
       0 1458.29     4.9 1459.17    15.8 1459.53      20 1459.19    22.8 1458.37
    28.5 1455.44    48.1  1443.3    51.1 1441.24    53.9 1439.53    54.81439.328
    59.6 1438.39    62.4  1438.6    66.61439.339    70.3 1439.75    75.8 1439.55
    83.4 1439.86    90.7  1440.5    97.6 1441.63     103 1442.98   108.5 1443.65
   112.8 1443.79   116.2 1444.62   135.7 1452.01   147.4 1457.06   157.5 1461.88
   167.2 1466.12   181.3 1473.29   189.3    1477   195.2 1479.55   206.2 1483.78
#Mann= 4 ,-1,0
       0     .07       0      30      .1       0    54.8    .045       0
    66.6      .1       0
Bank Sta=54.8,66.6
XS Rating Curve= 0 ,0
Exp/Cntr(USF)=0,0
Exp/Cntr=0.3,0.1

Type RM Length L Ch R = 1 ,7103    ,122.5,123.1,122.7
XS GIS Cut Line= 3
2197345.28206235759564.375631863 2197325.9518687759531.272057413
2197226.46555309759428.706367241
#Sta/Elev= 30
       0 1451.22     3.7  1452.5     8.3 1453.19    17.6 1453.37    22.2 1453.09
    26.9 1451.56    32.4  1448.1    35.3 1446.52    38.3 1445.13    46.7 1441.34
    49.6 1440.64    52.4 1440.06      58 1439.81    69.4  1439.8    80.3 1439.19
    86.3 1438.55    91.4 1437.09    94.8  1436.7      97 1436.74    98.6 1437.08
   100.5 1437.65   109.8 1441.75   115.6 1443.24   123.1 1445.54   128.8 1447.56
     136 1450.53   148.6 1456.78   158.3 1462.27   163.8 1465.68   181.2 1475.58
#Mann= 4 ,-1,0
       0     .06       0   78.33      .1       0    91.4    .045       0
    98.6      .1       0
Bank Sta=91.4,98.6
XS Rating Curve= 0 ,0
Exp/Cntr(USF)=0,0
Exp/Cntr=0.3,0.1

Type RM Length L Ch R = 1 ,6979    ,97.2,97.6,97.6
XS GIS Cut Line= 3
2197461.14439058759511.2484307872197439.58950556759480.709836252
2197333.84823574759366.371715226
#Sta/Elev= 30
       0 1451.78    12.3 1452.45    22.3 1452.04      27 1450.45    31.9 1447.21
    36.8  1444.6    48.3 1440.13    53.6  1438.9    60.1 1438.39    67.8  1438.1
    96.1 1438.29   102.1 1437.62   107.4 1437.28   110.11436.503   113.1 1435.63
   115.9 1435.89   118.21436.509   121.6 1437.66   123.9 1438.19     130 1438.67
   134.8 1439.32   138.5 1440.11   142.6  1441.3   152.7 1445.59   161.2 1448.79
   166.8 1451.39   172.5 1453.47   178.4 1455.98   183.8 1458.52   193.1  1463.5
#Mann= 4 ,-1,0
       0     .06       0   110.1    .045       0   118.2     .06       0
  127.38      .1       0
Bank Sta=110.1,118.2
XS Rating Curve= 0 ,0
Exp/Cntr(USF)=0,0
Exp/Cntr=0.3,0.1

Type RM Length L Ch R = 1 ,6882    ,121.8,122.5,122.6
XS GIS Cut Line= 2
2197517.36733781759425.951190257 2197405.9521462759304.787169373
#Sta/Elev= 30
       0 1446.53       1 1445.96     7.7 1442.92    12.7 1441.37    15.5 1440.73
    18.4 1440.28    22.8  1439.8    37.2 1438.93    43.1 1438.88    49.5 1438.69
    63.7 1437.67    71.7 1436.83    75.6    1436    77.1  1435.7    77.8 1435.67
    80.91435.995    86.3  1437.1    89.1 1437.36    94.8 1437.39     114 1437.19
     120 1437.37   125.9    1438   128.8 1438.99   131.5 1440.04   136.9 1443.34
   147.8  1450.2   149.5 1451.07   154.3 1453.22   158.6 1455.44   164.6 1458.37
#Mann= 4 ,-1,0
       0     .06       0      30      .1       0    75.6    .045       0
    80.9      .1       0
Bank Sta=75.6,80.9
XS Rating Curve= 0 ,0
Exp/Cntr(USF)=0,0
Exp/Cntr=0.3,0.1

Type RM Length L Ch R = 1 ,6759    ,176,174.6,171.5
XS GIS Cut Line= 2
2197615.55197542 759363.97648992 2197492.2989197759213.565981237
#Sta/Elev= 30
       0 1460.76     1.5  1460.2     4.4 1458.69    11.6 1453.72      14 1451.92
    18.6 1447.87    24.3 1442.32    27.1 1440.24    29.5 1438.69    32.8 1437.31
    35.7 1436.54    39.8 1436.16    50.2 1435.88    55.8 1436.08    64.1  1436.7
    66.9 1436.58    70.8 1435.96    74.7 1435.59    77.21435.946    81.2 1436.69
     100 1436.47   140.8 1436.91   150.5 1436.72     155 1436.88   158.8 1437.23
   163.1 1438.07   166.4 1439.52   169.1 1440.88     182 1448.03   194.5 1454.18
#Mann= 4 ,-1,0
       0     .06       0      70      .1       0    70.8    .045       0
    77.2      .1       0
Bank Sta=70.8,77.2
XS Rating Curve= 0 ,0
Exp/Cntr(USF)=0,0
Exp/Cntr=0.3,0.1

Type RM Length L Ch R = 1 ,6585    ,105.5,105.9,106.5
XS GIS Cut Line= 6
2197737.38544492759220.2624066172197702.46810597759200.662914377
2197692.52618439759189.4381713882197681.38164281759183.319599541
 2197595.1937827759112.2065583152197558.97080367759091.411904517
#Sta/Elev= 30
       0 1457.89     1.4 1457.54     3.2 1456.79       9 1453.96      12 1452.79
    28.9 1447.09    33.5 1445.22    38.4 1442.52    44.7 1438.76      50 1436.54
    55.4 1435.04      60 1434.56    63.2 1435.03    69.3    1436    71.1 1436.08
    95.2 1436.24   110.8 1435.96   121.2 1436.24   135.5 1437.79   147.1 1440.07
   152.3 1440.93   171.7  1443.5   178.1 1444.53   187.6 1445.03   192.2 1446.45
   196.8 1449.17   201.4 1451.56     206 1453.51   216.1 1458.15   221.3 1460.31
#Mann= 5 ,-1,0
       0      .1       0      20     .05       0    55.4    .045       0
    63.2     .05       0   77.75      .1       0
Bank Sta=55.4,63.2
XS Rating Curve= 0 ,0
Exp/Cntr(USF)=0,0
Exp/Cntr=0.3,0.1

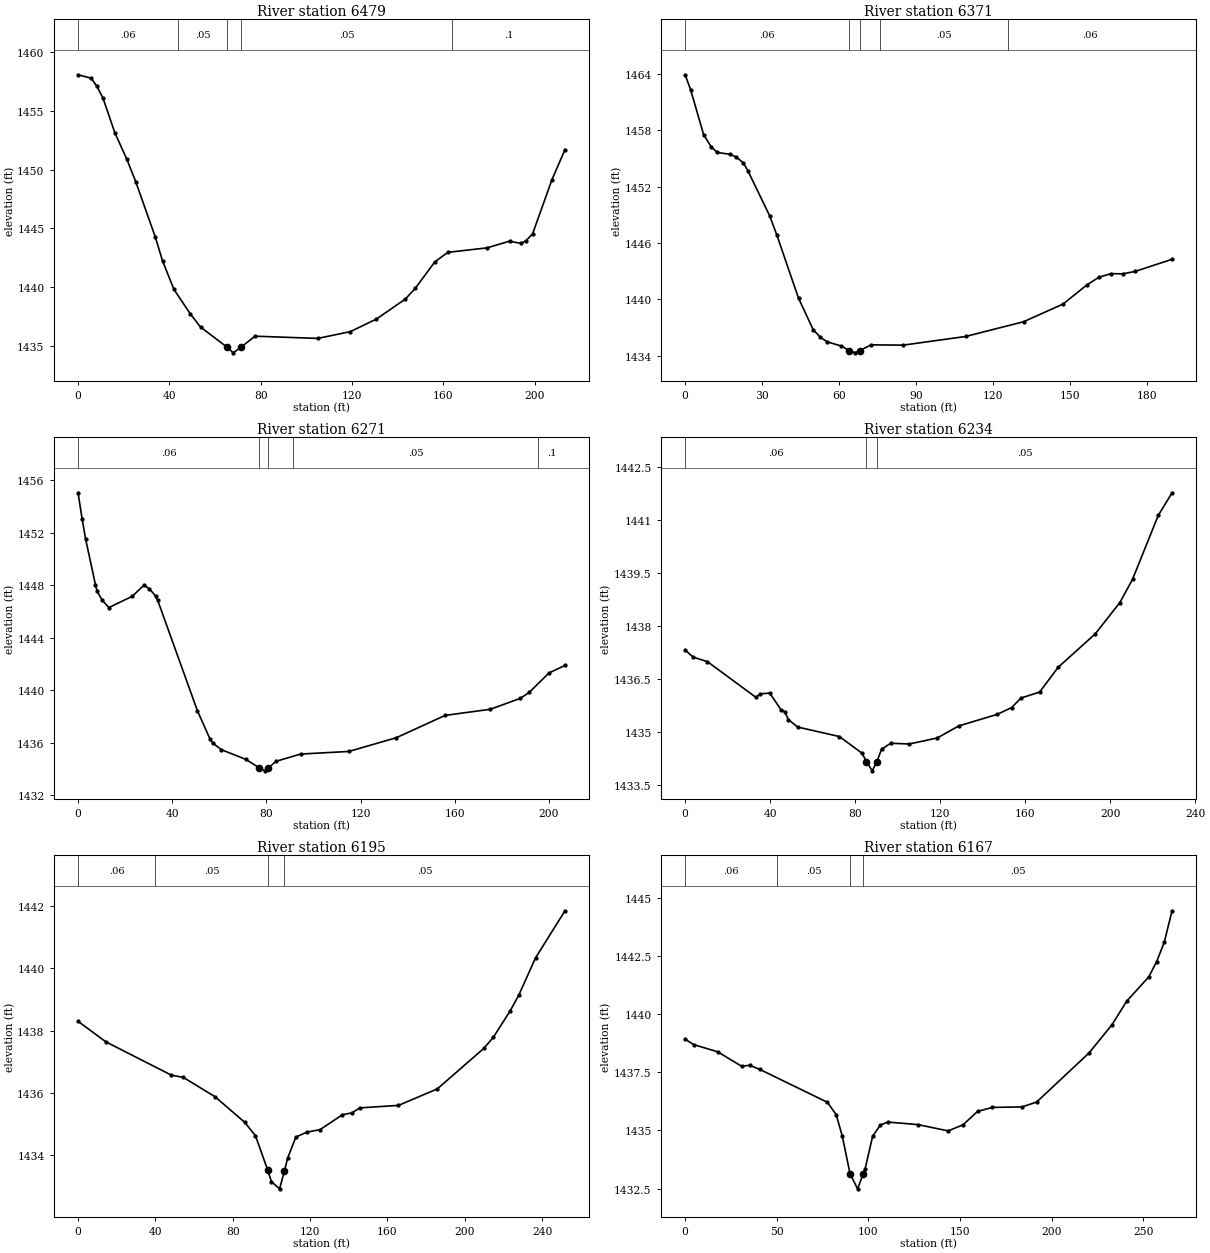
Type RM Length L Ch R = 1 ,6479    ,106.5,107.4,108
XS GIS Cut Line= 3
 2197800.5021366759148.4337260072197774.61272779759126.605400934
2197632.98243255759016.448504637
#Sta/Elev= 30
       0  1458.1     5.7 1457.81     8.2 1457.13    10.9 1456.12    16.1 1453.16
    21.4 1450.88    25.3 1448.96    33.9 1444.23      37 1442.23      42  1439.8
    49.2  1437.7    53.7 1436.58    65.1  1434.9      68 1434.39    71.41434.876
    77.5 1435.81     105 1435.62   119.3  1436.2   130.7 1437.27   143.4 1438.98
   147.8 1439.91   156.3 1442.15     162 1442.96   179.1 1443.34     189 1443.91
     194 1443.72   196.2 1443.95   199.1 1444.53   207.6 1449.16   213.3 1451.72
#Mann= 5 ,-1,0
       0     .06       0   43.86     .05       0    65.1    .045       0
    71.4     .05       0  163.86      .1       0
Bank Sta=65.1,71.4
XS Rating Curve= 0 ,0
Exp/Cntr(USF)=0,0
Exp/Cntr=0.3,0.1

Type RM Length L Ch R = 1 ,6371    ,101.8,100.5,98.6
XS GIS Cut Line= 4
2197861.92602808759065.6891449182197841.62060941 759049.44480998
2197757.35312192758970.7613126252197715.72701364758945.887174751
#Sta/Elev= 30
       0 1463.91     2.2 1462.26     7.2 1457.53    10.1 1456.26    12.5 1455.64
    17.6 1455.44      20 1455.14    22.7 1454.52    24.4 1453.72    32.9 1448.92
    35.7 1446.88    44.2 1440.12    49.9 1436.78    52.7 1435.97    55.3 1435.49
    60.8 1435.04      64 1434.55    66.3 1434.31      681434.542    72.5 1435.16
      85 1435.13   109.3 1436.05   131.9 1437.62   147.3  1439.5   156.6 1441.54
   161.3 1442.36     166 1442.74   170.6 1442.72   175.3 1442.97   189.8 1444.27
#Mann= 5 ,-1,0
       0     .06       0      64    .045       0      68     .06       0
      76     .05       0     126     .06       0
Bank Sta=64,68
XS Rating Curve= 0 ,0
Exp/Cntr(USF)=0,0
Exp/Cntr=0.3,0.1

Type RM Length L Ch R = 1 ,6271    ,37.8,36.9,36
XS GIS Cut Line= 4
2197936.00835121758995.7279707672197917.39505076758970.346197426
2197810.79160273758907.1737837792197761.72017428758891.944719775
#Sta/Elev= 30
       0 1455.06     1.7 1453.08     3.2 1451.53     7.4 1448.03     8.1 1447.53
    10.3 1446.85    13.1  1446.3      23 1447.16      28 1448.01    30.3 1447.73
    32.9 1447.19    33.8 1446.86    50.7 1438.42    56.1 1436.24    57.3 1435.95
    60.8 1435.46    71.2 1434.72      77 1434.06    79.4 1433.84    80.81434.051
      84 1434.56    94.5 1435.12     115 1435.32   135.2 1436.37   155.9 1438.07
   175.1 1438.54   187.8 1439.37   191.6 1439.82     200 1441.31   206.8 1441.88
#Mann= 5 ,-1,0
       0     .06       0      77    .045       0    80.8     .06       0
   91.48     .05       0  195.39      .1       0
Bank Sta=77,80.8
XS Rating Curve= 0 ,0
Exp/Cntr(USF)=0,0
Exp/Cntr=0.3,0.1

Type RM Length L Ch R = 1 ,6234    ,39.8,39,37.6
XS GIS Cut Line= 2
2197976.55805908758950.6897690292197767.20611162758857.594210535
#Sta/Elev= 30
       0 1437.31     3.7 1437.11    10.5 1436.98    33.3 1435.97    35.4 1436.07
    39.8 1436.09    45.1 1435.62    46.9 1435.56    48.6 1435.34    52.9 1435.13
    72.6 1434.86    83.2 1434.39    85.31434.153      88 1433.89    90.21434.145
    92.4  1434.5    96.7 1434.67   105.5 1434.65   118.6 1434.82   128.7 1435.16
   146.9 1435.49   153.6 1435.68     158 1435.95   166.8 1436.12   175.5 1436.82
     193 1437.77   204.5 1438.65   210.5 1439.31   222.6 1441.12   229.1 1441.76
#Mann= 3 ,-1,0
       0     .06       0    85.3    .045       0    90.2     .05       0
Bank Sta=85.3,90.2
XS Rating Curve= 0 ,0
Exp/Cntr(USF)=0,0
Exp/Cntr=0.3,0.1

Type RM Length L Ch R = 1 ,6195    ,28.5,27.8,28.1
XS GIS Cut Line= 5
 2198006.1220783758913.9039488112197946.50440457758890.256715095
2197875.22964379758868.6078391582197812.69413636758869.172275196
2197766.20676442758849.150406891
#Sta/Elev= 26
       0  1438.3    14.4 1437.64    48.3 1436.57    54.4  1436.5    70.8 1435.88
    86.1 1435.06    91.7 1434.63    98.11433.517     100 1433.15   104.2 1432.92
   106.71433.488   108.4 1433.91   112.6 1434.58   118.2 1434.74   125.1 1434.82
   136.7  1435.3   141.7 1435.36   145.7 1435.52   165.7  1435.6   185.8 1436.13
   209.8 1437.43   214.8 1437.79   223.5 1438.64   227.9 1439.14   236.6 1440.34
   251.8 1441.85
#Mann= 4 ,-1,0
       0     .06       0      40     .05       0    98.1    .045       0
   106.7     .05       0
Bank Sta=98.1,106.7
XS Rating Curve= 0 ,0
Exp/Cntr(USF)=0,0
Exp/Cntr=0.3,0.1

Type RM Length L Ch R = 1 ,6167    ,80.2,82.3,79
XS GIS Cut Line= 5
2198012.37792701758886.7665414022197961.62854312758864.410541572
2197878.82101545758843.4687895282197824.55408418758849.405695489
2197755.98345685758834.185860016
#Sta/Elev= 30
       0 1438.92     4.6 1438.69    17.7 1438.38    30.8 1437.76    35.2  1437.8
    40.8 1437.62    77.6 1436.21    82.4 1435.68    85.7 1434.77      90 1433.13
    94.1 1432.49    97.2 1433.14    98.2 1433.35   102.3 1434.75   106.5 1435.23
   110.6 1435.36   127.1 1435.25   143.5 1434.98   151.6 1435.24   159.6 1435.82
   167.7 1435.99   183.8 1436.01   191.8 1436.22   220.4 1438.33   232.9 1439.54
   240.9 1440.55     253  1441.6   257.3 1442.26   261.4 1443.08   265.7 1444.44
#Mann= 4 ,-1,0
       0     .06       0      50     .05       0      90    .045       0
    97.2     .05       0
Bank Sta=90,97.2
XS Rating Curve= 0 ,0
Exp/Cntr(USF)=0,0
Exp/Cntr=0.3,0.1

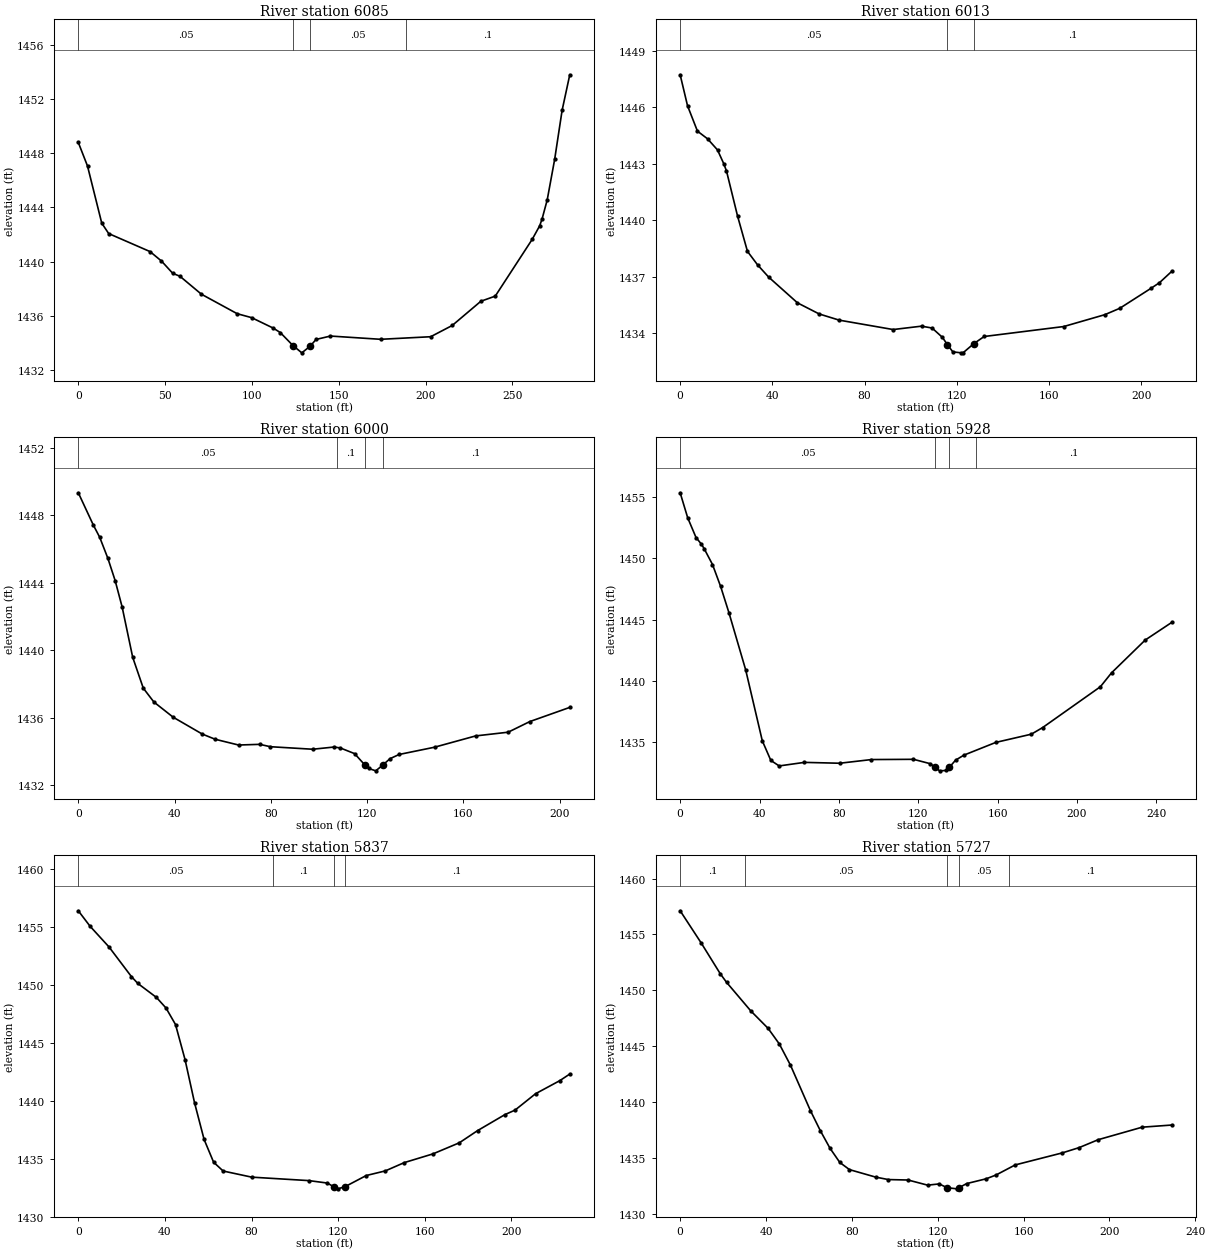
Type RM Length L Ch R = 1 ,6085    ,69.4,72.5,74
XS GIS Cut Line= 4
2198053.38810506758812.5171219642198015.15876744 758804.99659653
2197813.98471207758754.2330498492197780.14234762758740.445419887
#Sta/Elev= 30
       0  1448.8     5.3 1447.06    13.5 1442.84    17.5 1442.07    41.3 1440.74
    47.9 1440.04    54.4 1439.13    58.5 1438.92    70.9 1437.59    91.5 1436.15
    99.8 1435.86   112.2 1435.09   116.3 1434.76   123.6  1433.8   128.7 1433.26
   133.5 1433.75   136.9 1434.25   145.2  1434.5   174.1 1434.26   202.9 1434.45
   215.3 1435.28   231.8 1437.07   240.1 1437.45   261.4 1441.65   265.7 1442.65
   267.1 1443.17     270 1444.55   274.3 1447.55   278.6 1451.18     283  1453.8
#Mann= 4 ,-1,0
       0     .05       0   123.6    .045       0   133.5     .05       0
  188.96      .1       0
Bank Sta=123.6,133.5
XS Rating Curve= 0 ,0
Exp/Cntr(USF)=0,0
Exp/Cntr=0.3,0.1

Type RM Length L Ch R = 1 ,6013    ,12.9,12.6,12.3
XS GIS Cut Line= 3
2198055.10813894758768.5186014722197998.82106151758744.871367756
2197864.26497106758673.929666608
#Sta/Elev= 30
       0 1447.74     3.2 1446.09     7.5 1444.74    11.9 1444.33    16.2 1443.74
    18.9 1443.01    20.1 1442.62    24.9 1440.22    29.2 1438.34    33.6 1437.62
    38.4 1436.97    50.9  1435.6    60.3 1435.01      69 1434.68    92.4 1434.18
   104.7 1434.36   109.3 1434.26   113.8 1433.76   115.9 1433.38   118.3 1432.99
     122 1432.94   122.8 1432.95   127.4 1433.43   131.9 1433.81   166.4 1434.34
   184.2 1434.97   190.7 1435.31   204.2 1436.37   207.9 1436.67   213.2 1437.27
#Mann= 3 ,-1,0
       0     .05       0   115.9    .045       0   127.4      .1       0
Bank Sta=115.9,127.4
XS Rating Curve= 0 ,0
Exp/Cntr(USF)=0,0
Exp/Cntr=0.3,0.1

Type RM Length L Ch R = 1 ,6000    ,73.7,72.4,71.1
XS GIS Cut Line= 3
2198060.77015265758756.8615144292197963.18368112758712.231524035
2197877.58735626758666.935414382
#Sta/Elev= 30
       0 1449.32     6.2 1447.42     8.9 1446.68    12.3 1445.43    15.3 1444.12
    18.2 1442.56    22.6 1439.57      27 1437.74    31.4 1436.92    39.4 1436.02
    51.5 1435.02    56.9 1434.71    66.6 1434.37    75.4 1434.41    79.8 1434.27
    97.4 1434.12   106.2 1434.25   108.8  1434.2   114.8 1433.86   119.21433.166
   120.7 1432.98   123.6 1432.84   126.4 1433.17   129.5 1433.56   133.3 1433.81
     148 1434.24   165.1 1434.91   178.6 1435.13   187.6 1435.76   204.2  1436.6
#Mann= 4 ,-1,0
       0     .05       0  107.31      .1       0   119.2    .045       0
   126.4      .1       0
Bank Sta=119.2,126.4
XS Rating Curve= 0 ,0
Exp/Cntr(USF)=0,0
Exp/Cntr=0.3,0.1

Type RM Length L Ch R = 1 ,5928    ,88.8,90.2,90.9
XS GIS Cut Line= 4
 2198107.8563531758682.6440517692198079.89579158758674.831541934
2197940.50416875758626.7229287452197891.16200138758575.324837731
#Sta/Elev= 30
       0 1455.35     3.8 1453.31       8  1451.7    10.7 1451.16    12.1 1450.79
    16.3  1449.5    20.4 1447.71    24.6 1445.56      33 1440.92    41.4 1435.12
    45.7 1433.52    49.9 1433.07    62.6 1433.36    80.4 1433.29    96.4 1433.59
   117.6 1433.61   126.1 1433.25   128.4 1432.96   130.8 1432.67   133.9  1432.7
   135.71432.963   138.8 1433.54     143 1433.95   159.1 1434.99     177 1435.66
   182.7  1436.2   211.8 1439.53   217.4 1440.66   234.4 1443.34   247.7 1444.77
#Mann= 4 ,-1,0
       0     .05       0   128.4    .045       0   135.7     .05       0
  149.03      .1       0
Bank Sta=128.4,135.7
XS Rating Curve= 0 ,0
Exp/Cntr(USF)=0,0
Exp/Cntr=0.3,0.1

Type RM Length L Ch R = 1 ,5837    ,109.9,110.3,110.8
XS GIS Cut Line= 4
2198141.14473366758616.606987392 2198104.7955274758600.312515618
2198002.64172358758553.3092316552197931.82344241758529.494234447
#Sta/Elev= 30
       0 1456.43     5.4  1455.1    14.2  1453.3    24.5 1450.75    27.5 1450.15
    36.1 1448.94    40.5 1448.03    44.9  1446.6    49.3 1443.57    53.7 1439.83
    58.1 1436.67    62.5  1434.7    66.9 1433.94    80.1 1433.41   106.6 1433.11
     115  1432.9   118.1 1432.57   119.8  1432.4   123.11432.577     133 1433.55
   141.8 1433.95   150.6 1434.67   163.8 1435.42     176 1436.38   184.4 1437.43
   197.1 1438.82   201.7  1439.2   211.2 1440.62   222.4 1441.75     227 1442.32
#Mann= 4 ,-1,0
       0     .05       0   89.83      .1       0   118.1    .045       0
   123.1      .1       0
Bank Sta=118.1,123.1
XS Rating Curve= 0 ,0
Exp/Cntr(USF)=0,0
Exp/Cntr=0.3,0.1

Type RM Length L Ch R = 1 ,5727    ,102.3,102.9,103.5
XS GIS Cut Line= 4
2198191.69937686758540.0090431552198150.61502495758505.888140723
2198058.00114692758455.7513044952197991.15203195758434.164611119
#Sta/Elev= 30
       0 1457.12     9.8 1454.24    18.7 1451.48    21.6 1450.72    32.9 1448.16
      41 1446.59    46.2  1445.2    51.4  1443.3    60.7 1439.23    65.3 1437.44
    69.8 1435.87    74.4 1434.59    78.9 1433.95    91.1 1433.28      97 1433.06
   106.2 1433.02   115.3 1432.56   120.7 1432.67   124.4 1432.33     129 1432.23
   129.81432.321   133.5  1432.7   142.6 1433.13   147.2 1433.47   156.1 1434.37
   178.1 1435.45   185.9 1435.92   194.8 1436.63   215.3 1437.75     229 1437.94
#Mann= 5 ,-1,0
       0      .1       0      30     .05       0   124.4    .045       0
   129.8     .05       0  153.41      .1       0
Bank Sta=124.4,129.8
XS Rating Curve= 0 ,0
Exp/Cntr(USF)=0,0
Exp/Cntr=0.3,0.1

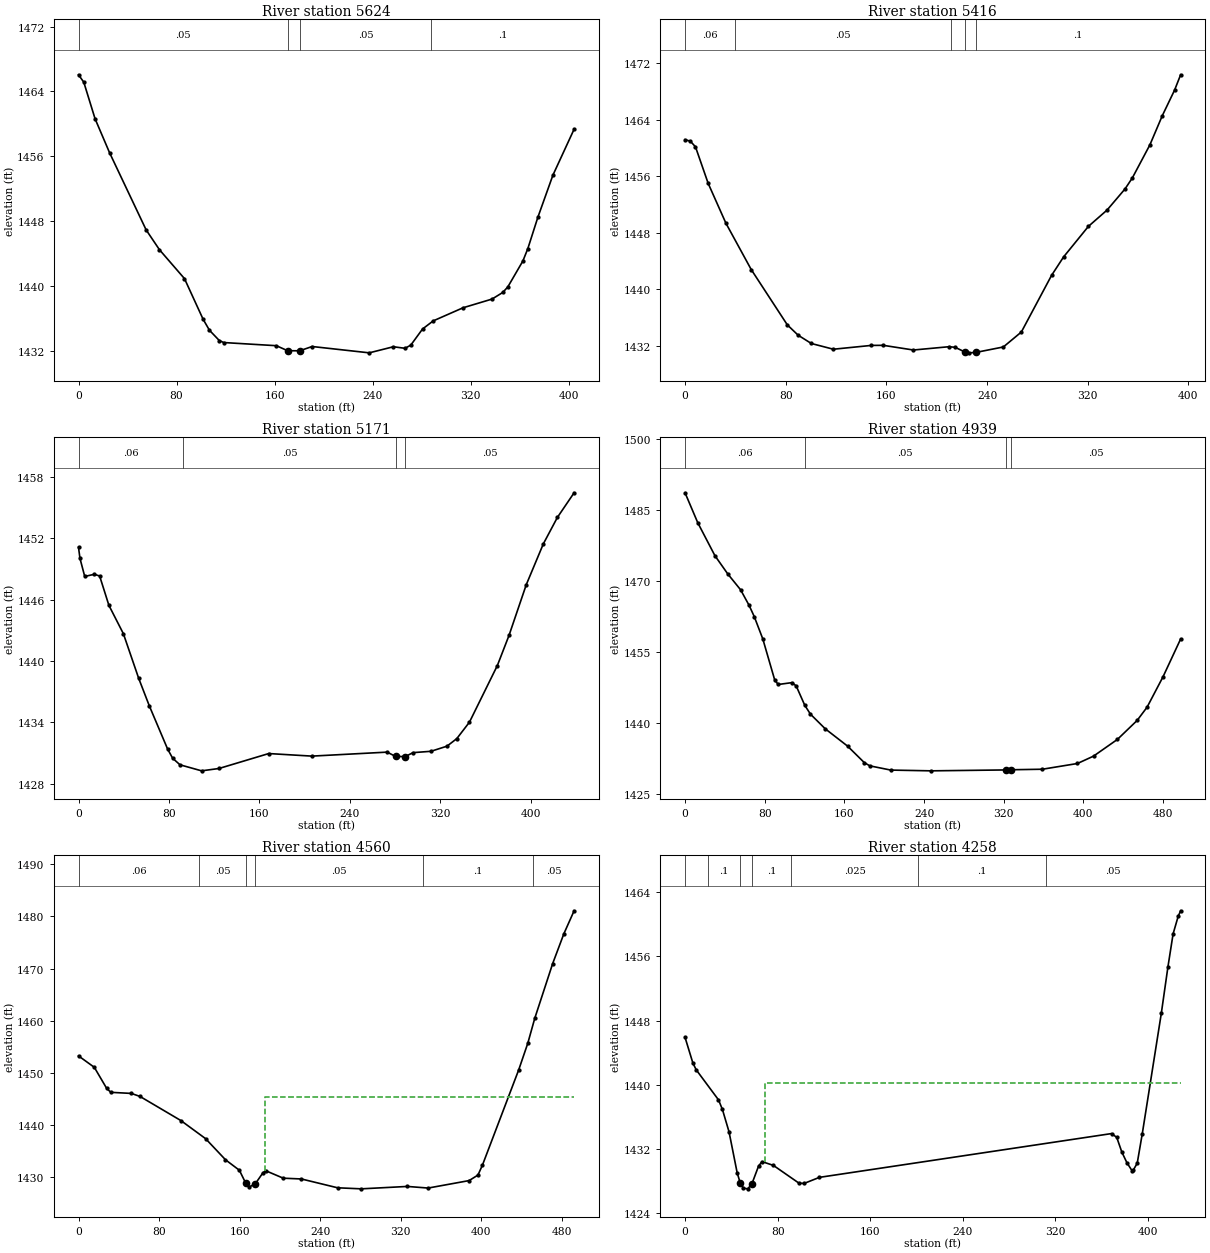
Type RM Length L Ch R = 1 ,5624    ,204.9,208.5,212.7
XS GIS Cut Line= 4
2198277.14374527758486.2507445032198219.49973275758434.009407725
2197996.87203439758292.7527293892197935.29556061758279.118830626
#Sta/Elev= 30
       0 1466.05     4.3 1465.14    13.5 1460.63    25.4 1456.42    55.2 1446.92
    66.1 1444.47    86.5 1440.91   101.7  1435.9   106.9 1434.54   114.9 1433.28
   118.5 1433.03   161.5 1432.64   170.7 1432.02   180.51432.014   190.7 1432.54
   237.3 1431.76     257 1432.51   266.5 1432.32   271.2 1432.71   280.8  1434.7
   289.5  1435.7   313.9 1437.32   337.5 1438.39   346.3 1439.21   350.4 1439.89
   362.7 1443.09   366.7  1444.6   374.9 1448.47   387.2 1453.67   404.5 1459.34
#Mann= 4 ,-1,0
       0     .05       0   170.7    .045       0   180.5     .05       0
  287.79      .1       0
Bank Sta=170.7,180.5
XS Rating Curve= 0 ,0
Exp/Cntr(USF)=0,0
Exp/Cntr=0.3,0.1

Type RM Length L Ch R = 1 ,5416    ,245.8,245.1,243.9
XS GIS Cut Line= 4
2198384.17068846758395.1729630032198348.42017218758358.189670302
2198220.21142415758160.945442561 2198158.5393535758073.233598245
#Sta/Elev= 30
       0 1461.16     4.2 1460.96     8.3 1460.16    18.4 1454.99    32.5 1449.36
    52.6 1442.82    81.3    1435    89.9 1433.54   100.4 1432.37   117.9 1431.56
   148.1  1432.1   157.6 1432.11   181.5 1431.45   210.1 1431.92   214.8 1431.82
   222.9 1431.13   225.8 1431.05   231.2 1431.11     253 1431.88   267.3 1433.99
   291.3 1441.99   300.9 1444.61   320.6 1448.92   335.4 1451.22   349.7 1454.21
   355.5 1455.76   369.5 1460.45   379.3 1464.55   389.1 1468.18   393.9 1470.34
#Mann= 5 ,-1,0
       0     .06       0      40     .05       0  211.44      .1       0
   222.9    .045       0   231.2      .1       0
Bank Sta=222.9,231.2
XS Rating Curve= 0 ,0
Exp/Cntr(USF)=0,0
Exp/Cntr=0.3,0.1

Type RM Length L Ch R = 1 ,5171    ,232.9,232.1,231
XS GIS Cut Line= 3
2198599.05904322758278.3520279842198580.56739687758229.040971049
2198338.94321789757928.243523743
#Sta/Elev= 30
       0  1451.1     1.3 1450.02     5.5 1448.26    14.1 1448.47    18.7  1448.3
    26.9 1445.43    39.7 1442.66    53.3 1438.28    62.7 1435.59    78.8 1431.39
    83.3 1430.48    89.8 1429.84   108.9 1429.25   124.3 1429.48   168.3 1430.94
   206.5 1430.69   273.1 1431.08   280.5 1430.66     289 1430.64     296 1431.03
   311.8 1431.16     326 1431.66   334.7  1432.4   345.9 1434.01   370.6 1439.55
   380.9 1442.49   396.2 1447.46   411.3 1451.45   423.7 1454.03   438.5 1456.44
#Mann= 4 ,-1,0
       0     .06       0   92.66     .05       0   280.5    .045       0
     289     .05       0
Bank Sta=280.5,289
XS Rating Curve= 0 ,0
Exp/Cntr(USF)=0,0
Exp/Cntr=0.3,0.1

Type RM Length L Ch R = 1 ,4939    ,379.4,378.3,376.1
XS GIS Cut Line= 3
2198868.07961492758082.5418420232198750.83522785758036.548211389
 2198484.8667756 757776.78875327
#Sta/Elev= 30
       0 1488.64    12.8 1482.31      30 1475.37    42.9 1471.52    55.8 1468.17
    64.3  1464.9    69.5 1462.52    78.1  1457.8    90.1 1449.11    93.6 1448.19
   107.3 1448.58   111.6  1447.9   120.2 1443.82   125.9 1441.94   140.8 1438.84
   163.2 1435.19     180 1431.71   185.6 1431.02   206.6 1430.13   247.1 1429.97
   322.1 1430.16   327.61430.199   358.9 1430.31   394.1 1431.52   410.2 1433.07
   434.2  1436.6     454  1440.6     464  1443.4     480 1449.81   497.7 1457.79
#Mann= 4 ,-1,0
       0     .06       0     120     .05       0   322.1    .045       0
   327.6     .05       0
Bank Sta=322.1,327.6
XS Rating Curve= 0 ,0
Exp/Cntr(USF)=0,0
Exp/Cntr=0.3,0.1

Type RM Length L Ch R = 1 ,4560    ,301,302.1,302.8
XS GIS Cut Line= 4
2199063.48681452757714.7068907332198934.35684637757686.358195702
2198886.41554102757650.7446545822198619.22354764757513.521309586
#Sta/Elev= 30
       0 1453.27    15.7 1451.08      28 1447.04    32.1 1446.29    52.5 1446.08
    61.1  1445.5   101.7 1440.88   126.2 1437.42     146 1433.37   159.8 1431.36
   166.1 1428.89   169.8 1428.17   175.8 1428.82   183.2 1430.87   186.1 1431.26
   203.4 1429.84   221.4 1429.69   257.4    1428   280.9  1427.8   326.7 1428.26
   347.3 1427.95     388 1429.38   396.8 1430.44   401.3 1432.37   437.3 1450.61
   446.3 1455.69   453.2 1460.46     471 1470.95   482.2  1476.7   492.3 1481.07
#Mann= 6 ,-1,0
       0     .06       0     120     .05       0   166.1    .045       0
   175.8     .05       0  341.93      .1       0  451.93     .05       0
#XS Ineff= 2 , 0
                          185.35         1445.33
Permanent Ineff=
       F       T
Bank Sta=166.1,175.8
XS Rating Curve= 0 ,0
Exp/Cntr(USF)=0,0
Exp/Cntr=0.3,0.1

Type RM Length L Ch R = 1 ,4258    ,319.2,318.3,318
XS GIS Cut Line= 3
 2199117.6618176757453.3601009672199064.36819778  757405.5227403
2198742.22800235757252.764340688
#Sta/Elev= 30
       0 1445.92     6.8 1442.71     9.7 1441.87    28.9 1438.14    32.3 1436.94
      38 1434.16      45 1429.08    47.81427.728    50.4 1427.14    54.2 1427.06
    57.8  1427.7    63.5 1429.89    66.5 1430.45    76.3 1429.98    98.4 1427.77
   102.8 1427.73   116.1 1428.49   368.4 1433.94   372.9 1433.47   377.3 1431.64
   381.7 1430.31   386.1 1429.32   387.3 1429.42   390.6 1430.25     395 1433.95
   411.4  1448.9   417.1 1454.67   421.6 1458.81     426    1461   428.1 1461.68
#Mann= 7 ,-1,0
       0     .06       0      20      .1       0    47.8    .045       0
    57.8      .1       0   91.61    .025       0  201.61      .1       0
  311.61     .05       0
#XS Ineff= 2 , 0
                           68.73         1440.28
Permanent Ineff=
       F       T
Bank Sta=47.8,57.8
XS Rating Curve= 0 ,0
Exp/Cntr(USF)=0,0
Exp/Cntr=0.3,0.1

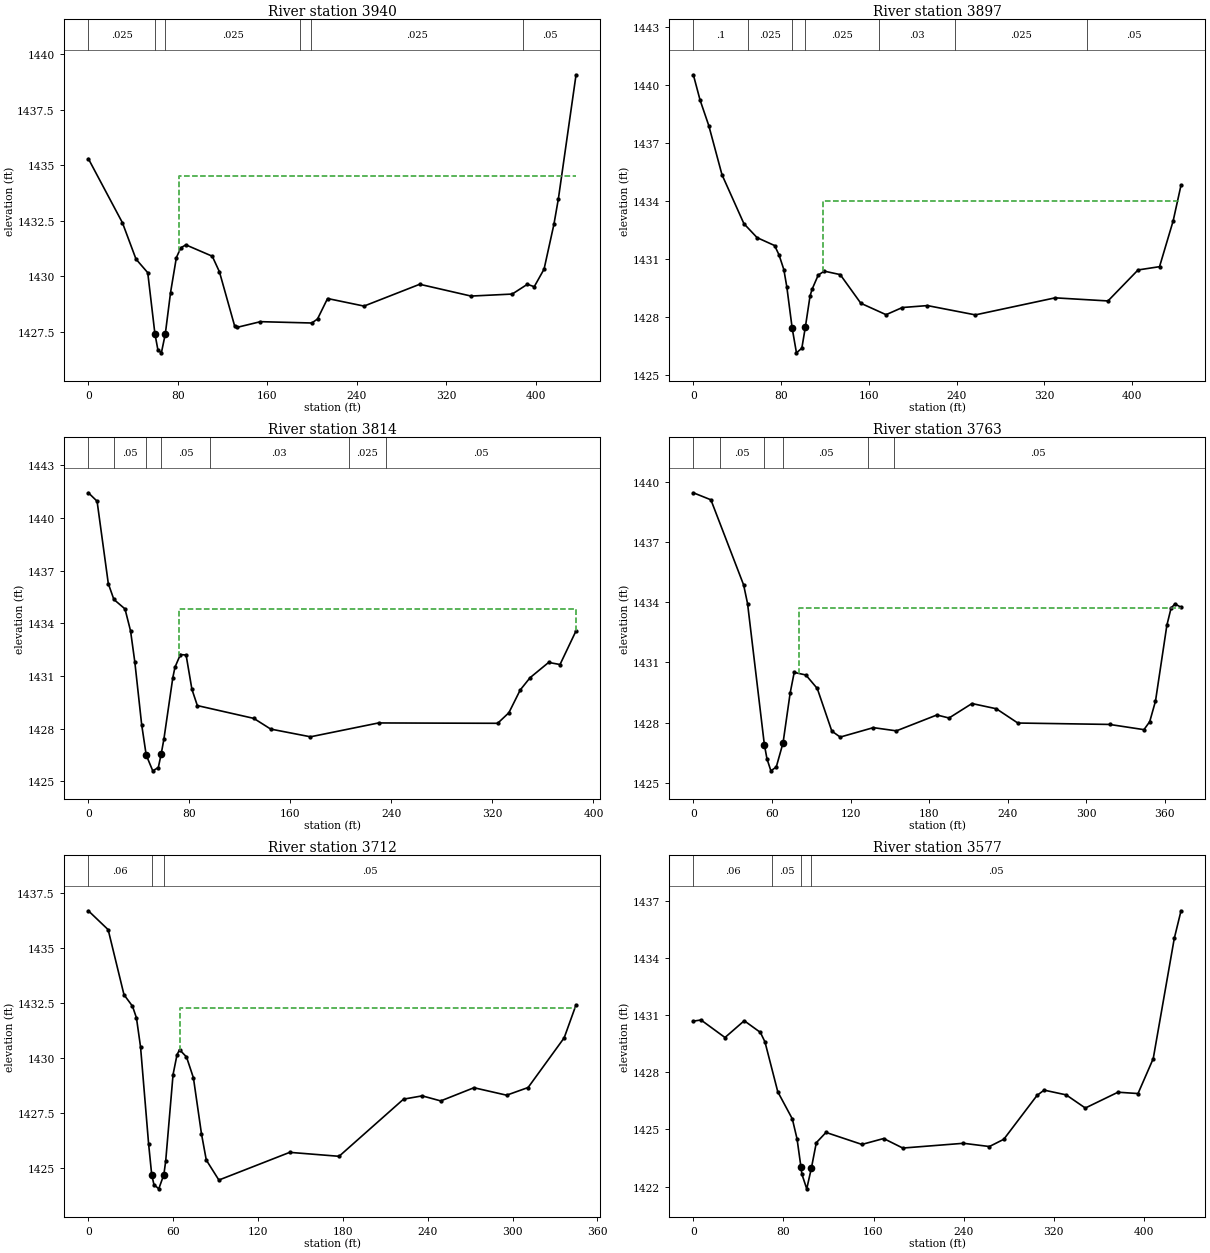
Type RM Length L Ch R = 1 ,3940    ,40.7,42.6,43.9
XS GIS Cut Line= 5
 2199225.1912441757195.5950276922199229.89277093757142.741772478
2199213.60490606757130.3312212872199209.74467834757074.910515212
2198942.46574268756923.927159293
#Sta/Elev= 30
       0 1435.29    30.5 1432.41    42.6 1430.78    53.1 1430.17    59.5 1427.43
    62.2  1426.7    65.3 1426.57    68.8 1427.42    73.5 1429.28    78.7 1430.85
    82.7 1431.29    87.2 1431.42   110.8 1430.91   117.2 1430.21   130.9 1427.76
   132.6 1427.71   153.9 1427.97   199.8 1427.91   204.9 1428.09   213.9 1429.01
   246.5 1428.67   296.3 1429.65   342.2 1429.12     379 1429.21   392.6 1429.65
   398.7 1429.54   407.5 1430.33   416.3 1432.34   420.3 1433.49   436.1 1439.06
#Mann= 6 ,-1,0
       0    .025       0    59.5    .045       0    68.8    .025       0
  189.09     .03       0  199.09    .025       0  389.09     .05       0
#XS Ineff= 2 , 0
                           81.13         1434.53
Permanent Ineff=
       F       T
Bank Sta=59.5,68.8
XS Rating Curve= 0 ,0
Exp/Cntr(USF)=0,0
Exp/Cntr=0.3,0.1

Type RM Length L Ch R = 1 ,3897    ,87,83.4,78.7
XS GIS Cut Line= 5
2199252.87098982757191.3151689892199252.82771765757109.932069871
2199234.82441896757092.6287591732199231.84200446757060.309965296
2198971.48477652756899.925928916
#Sta/Elev= 30
       0 1440.51     6.1 1439.21    14.1 1437.88    26.1 1435.35    46.1 1432.82
    58.1  1432.1    74.1 1431.69    78.1 1431.21    82.5 1430.45    85.2 1429.56
    90.11427.424      94 1426.15    98.9 1426.39   102.2 1427.51   106.4 1429.09
   108.3 1429.44   113.8 1430.16   119.3 1430.37   133.9 1430.19   152.7 1428.71
   175.7 1428.12   190.5 1428.49   213.4 1428.59   257.1 1428.11   329.8 1428.99
     378 1428.83   405.4 1430.43     425  1430.6   437.4 1432.96   444.6 1434.81
#Mann= 7 ,-1,0
       0      .1       0      50    .025       0    90.1    .045       0
   102.2    .025       0  168.81     .03       0  238.81    .025       0
  358.81     .05       0
#XS Ineff= 2 , 0
                          118.03         1433.98
Permanent Ineff=
       F       T
Bank Sta=90.1,102.2
XS Rating Curve= 0 ,0
Exp/Cntr(USF)=0,0
Exp/Cntr=0.3,0.1

Type RM Length L Ch R = 1 ,3814    ,50.1,50.6,51.3
XS GIS Cut Line= 3
2199334.48406451757051.6722239392199247.32845871757011.410724078
2198988.85049638756879.574939391
#Sta/Elev= 30
       0 1441.44     6.9 1440.96    15.8 1436.26    20.2 1435.36      29 1434.82
    33.4 1433.57    36.8 1431.79    42.2 1428.23    45.8 1426.49      51 1425.59
    55.4 1425.78    57.71426.562    59.8 1427.39    66.9 1430.91    68.6  1431.5
    72.9 1432.22    77.4 1432.19      82 1430.24    86.3 1429.31     131 1428.58
   144.4 1427.97   175.9 1427.53   229.8 1428.32   324.1  1428.3     333  1428.9
     342  1430.2   349.8  1430.9   364.5 1431.77   373.5 1431.65   386.2 1433.57
#Mann= 7 ,-1,0
       0    .025       0      20     .05       0    45.8    .045       0
    57.7     .05       0   96.01     .03       0  206.01    .025       0
  236.01     .05       0
#XS Ineff= 2 , 0
                           71.89         1434.81
Permanent Ineff=
       F       F
Bank Sta=45.8,57.7
XS Rating Curve= 0 ,0
Exp/Cntr(USF)=0,0
Exp/Cntr=0.3,0.1

Type RM Length L Ch R = 1 ,3763    ,49.7,50.9,53
XS GIS Cut Line= 3
2199364.04674149757013.2905405282199290.55636976756974.289867967
2199026.31825389756857.016562664
#Sta/Elev= 30
       0 1439.44    13.4 1439.09    38.4 1434.85    41.4 1433.92    54.2 1426.91
    56.2  1426.2    59.2  1425.6    63.3 1425.79    68.5    1427    73.9 1429.47
      77  1430.5    85.9 1430.37    94.6  1429.7   105.7 1427.58   112.1 1427.28
   137.4 1427.75     155 1427.59   185.9 1428.38   195.2 1428.23   212.7 1428.95
   231.3 1428.69   247.7 1427.98   317.7 1427.91     344 1427.65   348.4 1428.05
   352.8 1429.07   361.5 1432.85   364.7  1433.7   367.7 1433.91   372.3 1433.74
#Mann= 6 ,-1,0
       0     .06       0      20     .05       0    54.2    .045       0
    68.5     .05       0   133.2     .03       0   153.2     .05       0
#XS Ineff= 2 , 0
                            80.9         1433.69
Permanent Ineff=
       F       F
Bank Sta=54.2,68.5
XS Rating Curve= 0 ,0
Exp/Cntr(USF)=0,0
Exp/Cntr=0.3,0.1

Type RM Length L Ch R = 1 ,3712    ,137.9,135.6,132.7
XS GIS Cut Line= 3
2199380.74811188756972.0589429292199317.01447901756926.828622833
2199072.41493683756820.322457147
#Sta/Elev= 30
       0 1436.69      14 1435.83    25.2 1432.87    31.2 1432.35      34 1431.82
    36.9  1430.5    42.6 1426.09    44.8 1424.68    46.4 1424.23    49.8 1424.04
    53.4 1424.69    54.7 1425.31    59.9 1429.24    62.7 1430.14    64.5 1430.37
    69.4 1430.04    74.3 1429.09      80 1426.54    83.4 1425.35    92.3 1424.44
   142.4  1425.7   177.3 1425.52   222.9 1428.12   236.1 1428.27   249.2 1428.04
   272.7 1428.64   295.8  1428.3     311 1428.65   336.5 1430.91   344.9 1432.41
#Mann= 3 ,-1,0
       0     .06       0    44.8    .045       0    53.4     .05       0
#XS Ineff= 2 , 0
                           65.07         1432.25
Permanent Ineff=
       F       F
Bank Sta=44.8,53.4
XS Rating Curve= 0 ,0
Exp/Cntr(USF)=0,0
Exp/Cntr=0.3,0.1

Type RM Length L Ch R = 1 ,3577    ,113.8,113.7,113.2
XS GIS Cut Line= 3
2199510.53099878756867.3491548142199201.97938777756752.516030975
2199104.12159528756717.566819371
#Sta/Elev= 30
       0 1430.68     6.8 1430.74    28.1 1429.82    45.2  1430.7    59.5 1430.09
    63.6 1429.59      75 1426.97    87.9 1425.55    92.1  1424.5    95.5 1423.05
    96.4 1422.65   100.7 1421.88   104.9 1422.99   109.2  1424.3   117.8 1424.84
   149.7 1424.21     169 1424.52     186 1424.02   239.9 1424.27   262.9  1424.1
   275.7 1424.48   305.2 1426.78   311.5 1427.06   331.1 1426.81   348.1 1426.12
   377.1 1426.95   394.9 1426.88   408.4 1428.71   427.1 1435.02   433.1 1436.47
#Mann= 4 ,-1,0
       0     .06       0      70     .05       0    95.5    .045       0
   104.9     .05       0
Bank Sta=95.5,104.9
XS Rating Curve= 0 ,0
Exp/Cntr(USF)=0,0
Exp/Cntr=0.3,0.1