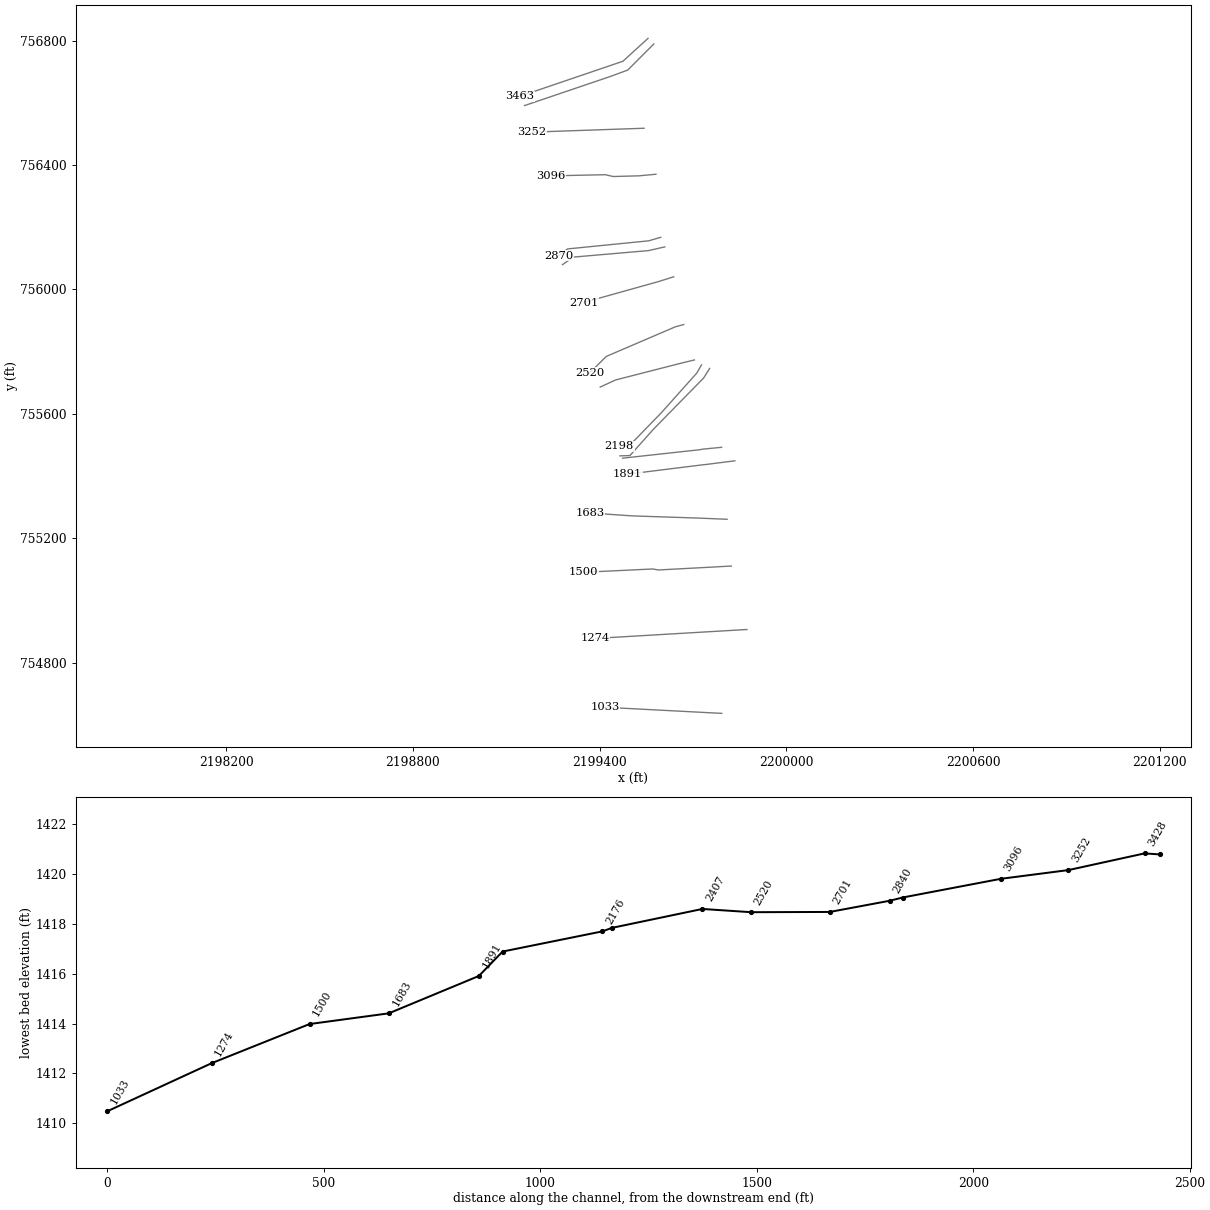
HEC-RAS study LIPECKSRN.prj: LIPECKSRN

--- LIPECKSRN.g01 (geometry) --- (continued)

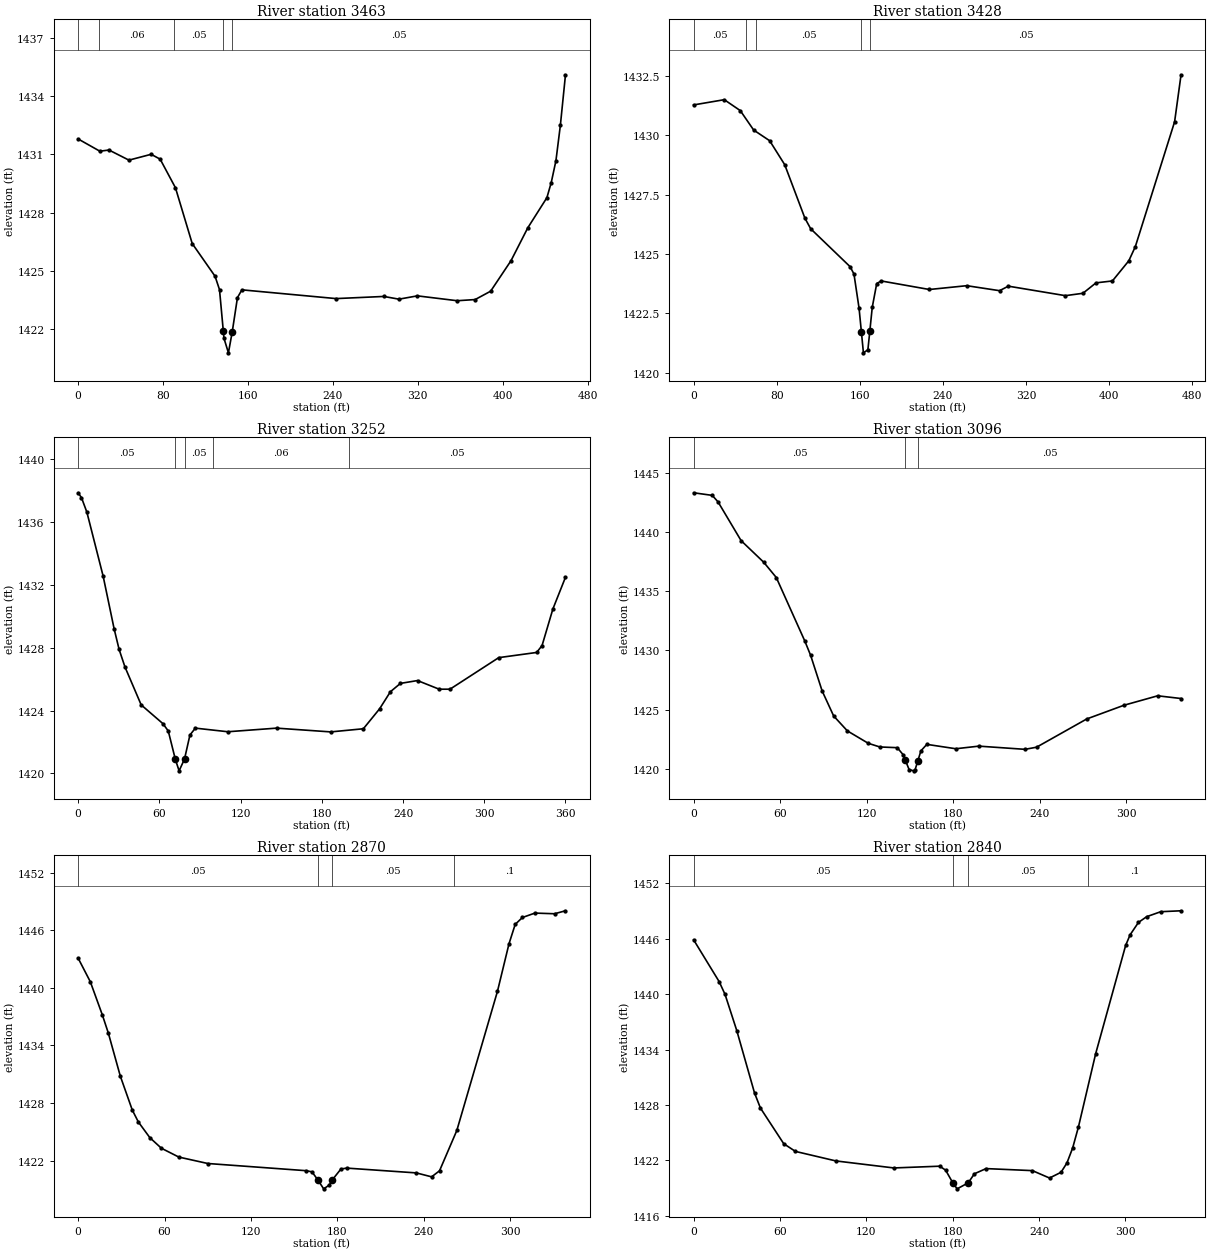
Type RM Length L Ch R = 1 ,3463    ,34.2,34.6,34.6
XS GIS Cut Line= 3
 2199555.5267909756807.0017083582199474.92636048756733.395530173
2199143.60921498 756620.67486335
#Sta/Elev= 30
       0 1431.79    20.5 1431.16    29.1 1431.22    47.9  1430.7    68.8    1431
    77.3 1430.75    91.7 1429.28   107.5 1426.41     129 1424.73   133.2 1424.04
   136.8  1421.9   137.4 1421.54   141.6 1420.79   145.2 1421.87   150.1 1423.63
   154.3 1424.03     243 1423.58     288 1423.69   302.2 1423.55   319.6 1423.72
   357.1 1423.47     374 1423.53   388.6 1423.96   407.8 1425.53   423.6 1427.22
   441.6 1428.77   445.7 1429.55   450.1 1430.67   454.3  1432.5   459.1 1435.09
#Mann= 5 ,-1,0
       0     .05       0      20     .06       0      90     .05       0
   136.8    .045       0   145.2     .05       0
Bank Sta=136.8,145.2
XS Rating Curve= 0 ,0
Exp/Cntr(USF)=0,0
Exp/Cntr=0.3,0.1

Type RM Length L Ch R = 1 ,3428    ,178.7,176,172.9
XS GIS Cut Line= 4
2199574.14435737756788.9379216912199490.22998365756704.953605441
2199433.26013397756684.0241383052199158.60160762756590.858494797
#Sta/Elev= 30
       0 1431.28    29.5  1431.5    44.9 1431.04    57.8 1430.22    73.2 1429.77
    87.7 1428.76   107.1 1426.51   112.7 1426.06   150.7 1424.46   154.4 1424.15
   159.3 1422.71   161.51421.729   163.5 1420.83   167.8 1420.96   169.7 1421.76
     172 1422.75   176.3 1423.75   180.6 1423.86     227  1423.5     263 1423.66
   294.6 1423.45   303.1 1423.64     358 1423.24   374.9 1423.34   387.5 1423.78
   403.3 1423.86   419.1 1424.71   425.4 1425.31   463.2 1430.57   469.4 1432.55
#Mann= 5 ,-1,0
       0     .05       0      50     .06       0      60     .05       0
   161.5    .045       0   169.7     .05       0
Bank Sta=161.5,169.7
XS Rating Curve= 0 ,0
Exp/Cntr(USF)=0,0
Exp/Cntr=0.3,0.1

Type RM Length L Ch R = 1 ,3252    ,157.7,155.9,153.3
XS GIS Cut Line= 2
2199542.71268576756517.9812127322199182.88306547756505.537394737
#Sta/Elev= 30
       0 1437.87     2.5 1437.56     6.5 1436.63    18.5 1432.56    26.6 1429.21
    30.3 1427.89    34.6 1426.78    46.6 1424.36    62.6 1423.17    66.6  1422.7
    71.81420.902    74.6 1420.16    78.6 1420.91    82.6 1422.44    86.6 1422.88
   110.6 1422.65   146.6 1422.88   186.6 1422.64   210.7 1422.84   222.7 1424.11
   230.7  1425.2   238.1 1425.73   250.7 1425.91   266.7 1425.36   274.7 1425.36
   310.7 1427.37   338.7  1427.7   342.7 1428.14   350.7 1430.47     360 1432.49
#Mann= 5 ,-1,0
       0     .05       0    71.8    .045       0    78.6     .05       0
     100     .06       0     200     .05       0
Bank Sta=71.8,78.6
XS Rating Curve= 0 ,0
Exp/Cntr(USF)=0,0
Exp/Cntr=0.3,0.1

Type RM Length L Ch R = 1 ,3096    ,223.2,226.6,229.5
XS GIS Cut Line= 5
2199580.98367827 756370.090021582199525.66007485756364.994426528
2199443.40261187756362.8106000782199418.65257876 756368.63413728
 2199243.9464627756364.994426528
#Sta/Elev= 30
       0 1443.34    12.9 1443.12    16.9 1442.57    32.9 1439.29    48.6 1437.46
    57.3 1436.17    77.1 1430.79    81.1 1429.59    89.1 1426.57    97.1 1424.45
   106.6 1423.19   121.1 1422.14   129.1 1421.83   141.2 1421.77   145.3 1421.17
   146.81420.715   149.4 1419.92   152.5 1419.81   153.5 1419.88   155.5 1420.67
   157.6  1421.5   161.7 1422.05   181.8 1421.68   197.8  1421.9   229.8 1421.63
   237.8 1421.81   272.6  1424.2   298.4 1425.36   321.8 1426.16     338 1425.93
#Mann= 3 ,-1,0
       0     .05       0   146.8    .045       0   155.5     .05       0
Bank Sta=146.8,155.5
XS Rating Curve= 0 ,0
Exp/Cntr(USF)=0,0
Exp/Cntr=0.3,0.1

Type RM Length L Ch R = 1 ,2870    ,29.9,29.8,29.7
XS GIS Cut Line= 4
2199596.31747082 756167.37083676 2199557.3987517756156.090048608
 2199297.3765848756130.144235859 2199268.0465356 756108.71073837
#Sta/Elev= 30
       0  1443.1     8.5 1440.63    16.8 1437.19      21 1435.28    29.3  1430.8
    37.6 1427.27    41.8 1426.03    49.8 1424.39    57.8 1423.29    69.9 1422.37
      90  1421.7   158.3 1420.95   162.3 1420.83   166.4 1419.98   170.4 1419.06
   174.4 1419.46  176.331419.985   182.4 1421.13   186.5 1421.22   234.7 1420.72
   245.3 1420.31   250.8 1420.94   262.8 1425.14     291 1439.64     299 1444.59
   303.3 1446.61   308.3 1447.33     317 1447.79   330.6 1447.72   338.2 1448.03
#Mann= 4 ,-1,0
       0     .05       0   166.4    .045       0  176.33     .05       0
  260.52      .1       0
Bank Sta=166.4,176.33
XS Rating Curve= 0 ,0
Exp/Cntr(USF)=0,0
Exp/Cntr=0.3,0.1

Type RM Length L Ch R = 1 ,2840    ,136.3,138.7,140.6
XS GIS Cut Line= 4
2199609.43995787756136.5981476862199556.90827739756124.674653786
2199315.49941093756103.8051957042199280.52896766756079.551501177
#Sta/Elev= 30
       0 1445.86    17.7 1441.35    21.8 1439.97      30 1436.03    42.3  1429.3
    46.4 1427.67    62.6 1423.81    70.7 1422.98    98.8 1421.95   139.1 1421.19
     171 1421.38   175.1 1420.95   180.11419.575   183.1 1418.93   190.8 1419.58
   195.1 1420.56   203.2 1421.12   235.4  1420.9   247.3  1420.1   255.3 1420.72
   259.4 1421.73   263.4 1423.36   267.4 1425.63   279.4 1433.57   300.2 1445.26
   303.3 1446.41   309.1 1447.75   314.8 1448.37   324.6 1448.91   338.7 1449.01
#Mann= 4 ,-1,0
       0     .05       0   180.1    .045       0   190.8     .05       0
  273.87      .1       0
Bank Sta=180.1,190.8
XS Rating Curve= 0 ,0
Exp/Cntr(USF)=0,0
Exp/Cntr=0.3,0.1

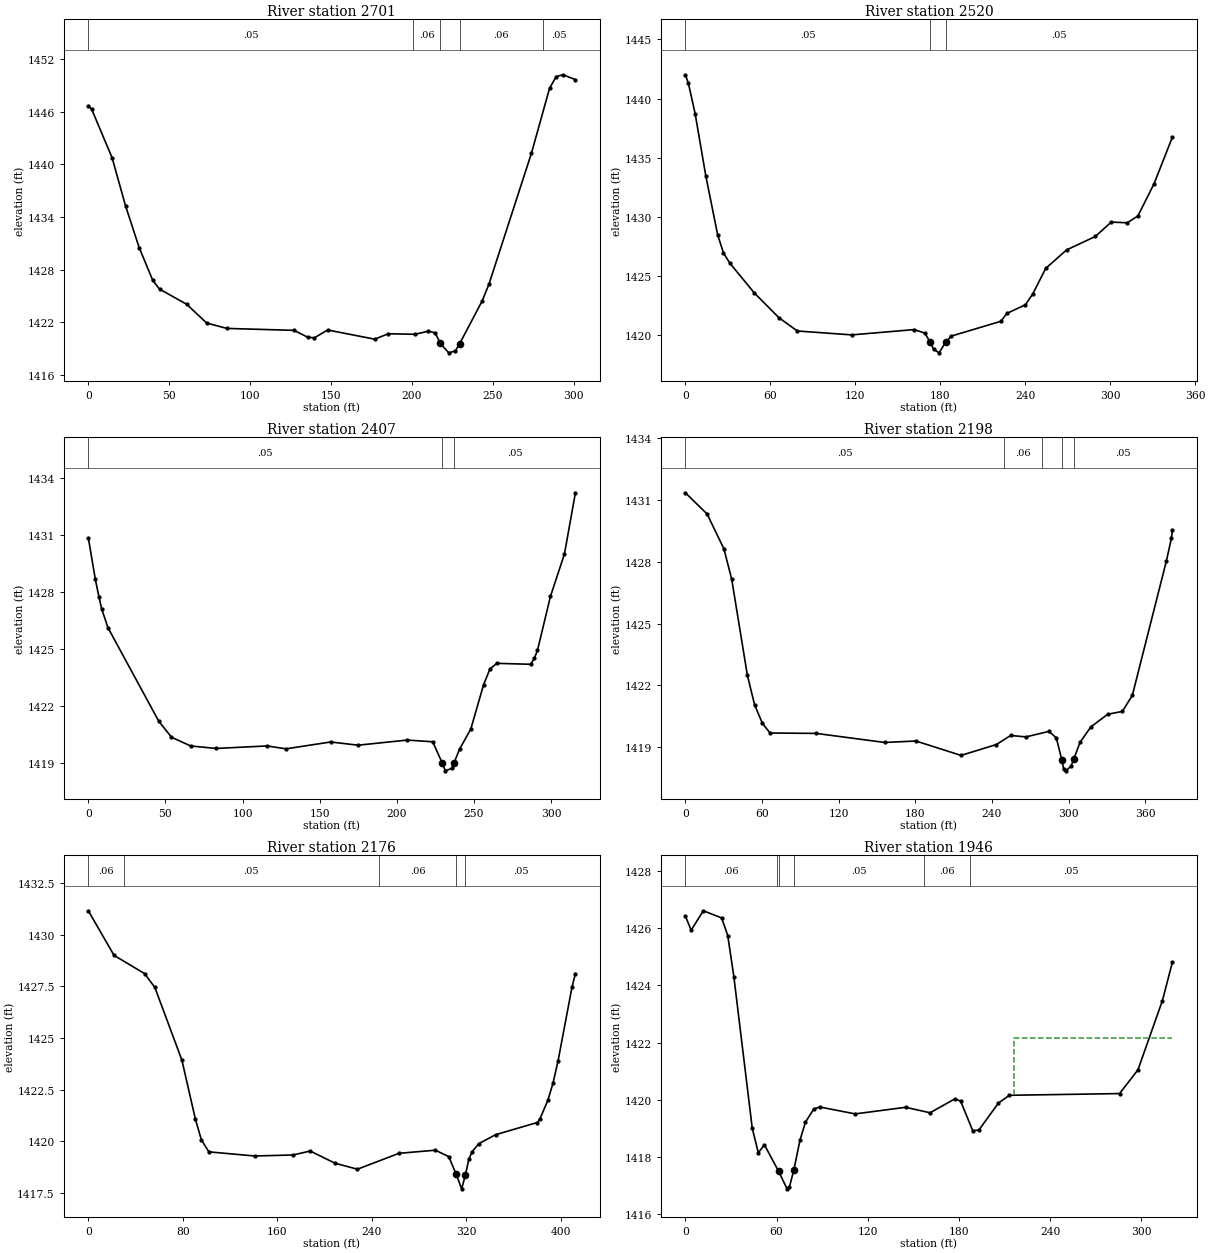
Type RM Length L Ch R = 1 ,2701    ,179.6,181.4,182.6
XS GIS Cut Line= 3
2199638.15062117756040.5266777892199589.62114449756025.248879574
 2199348.7711491755957.846828625
#Sta/Elev= 30
       0 1446.72     2.1  1446.3    14.7 1440.76      23 1435.27    31.4 1430.51
    39.8 1426.77      44 1425.76    60.7 1424.04    73.1 1421.89    85.6 1421.27
   127.1 1421.05   135.5 1420.27   139.6 1420.19   147.9 1421.09     177 1420.04
   185.3 1420.66   201.9  1420.6   210.2 1420.96   214.4 1420.75   217.5 1419.57
   222.7 1418.48   226.8  1418.7   229.51419.537   243.4 1424.42   247.6 1426.34
   273.8 1441.27     285 1448.69   289.1 1450.04   293.3 1450.25     301  1449.7
#Mann= 5 ,-1,0
       0     .05       0  200.88     .06       0   217.5    .045       0
   229.5     .06       0  280.88     .05       0
Bank Sta=217.5,229.5
XS Rating Curve= 0 ,0
Exp/Cntr(USF)=0,0
Exp/Cntr=0.3,0.1

Type RM Length L Ch R = 1 ,2520    ,116,112.7,110.6
XS GIS Cut Line= 4
2199670.20122935755886.955162947 2199643.6398794755879.830092333
2199421.47102384 755784.570103492199368.28886305755732.000190332
#Sta/Elev= 30
       0 1442.01     2.1 1441.31     6.9 1438.72    14.5 1433.41    22.8 1428.46
    26.9 1426.93    31.3 1426.08    48.7 1423.54    66.1 1421.44    79.1 1420.32
   117.4 1419.99   161.8 1420.44   169.2 1420.13   172.71419.415   175.3 1418.78
   179.2 1418.47  183.861419.386   187.9 1419.89   222.8 1421.14   227.1 1421.81
   240.2 1422.54   245.4 1423.47   254.5 1425.62   269.2 1427.18   289.5 1428.32
   300.8 1429.54   312.1 1429.48   319.6 1430.06     331 1432.78     344 1436.74
#Mann= 3 ,0,0
       0     .05       0   172.7    .045       0  183.86     .05       0
Bank Sta=172.7,183.86
XS Rating Curve= 0 ,0
Exp/Cntr(USF)=0,0
Exp/Cntr=0.3,0.1

Type RM Length L Ch R = 1 ,2407    ,202.8,209.1,212.6
XS GIS Cut Line= 4
2199704.50221453 755773.170925582199663.88304255755763.343706552
2199451.61511153755708.9664279282199401.82386846755686.036250195
#Sta/Elev= 30
       0 1430.87     4.5  1428.7     6.9 1427.75     8.6 1427.14    12.7 1426.14
    45.6 1421.22    53.9 1420.37    66.3 1419.91    82.8 1419.78   115.8 1419.91
   128.2 1419.76   157.1 1420.12   174.8 1419.95   206.7 1420.22   223.2 1420.13
   229.4 1419.01   231.4  1418.6   235.6 1418.73     2371419.013   240.6 1419.74
   247.9  1420.8   256.2 1423.14   260.3 1423.96   264.7 1424.26   286.7 1424.21
   289.1 1424.53   291.1 1424.94   299.5 1427.78   308.6 1430.02   315.7 1433.24
#Mann= 3 ,-1,0
       0     .05       0   229.4    .045       0     237     .05       0
Bank Sta=229.4,237
XS Rating Curve= 0 ,0
Exp/Cntr(USF)=0,0
Exp/Cntr=0.3,0.1

Type RM Length L Ch R = 1 ,2198    ,21.6,21.9,21.8
XS GIS Cut Line= 5
2199727.41556282755757.1360023342199712.30313009755731.161703984
2199599.50974385755604.7209801762199494.68319049755496.798181507
2199463.34208256755496.299872385
#Sta/Elev= 30
       0 1431.36      17 1430.33    30.2 1428.63    36.3 1427.15    48.5  1422.5
    54.2 1421.05    60.3 1420.15    66.3 1419.68   102.4 1419.66     156 1419.22
   180.5 1419.29   215.8 1418.59   243.5 1419.12   254.6 1419.56   266.6 1419.49
   284.7 1419.76   290.4 1419.44   294.71418.368   296.1 1417.94   297.7 1417.84
   301.9 1418.06   304.11418.424     309 1419.23   317.5 1419.98   330.6 1420.59
   342.1 1420.73   349.9 1421.51   376.5 1428.03   380.5 1429.15   381.3 1429.56
#Mann= 5 ,-1,0
       0     .05       0  249.49     .06       0  279.49     .05       0
   294.7    .045       0   304.1     .05       0
Bank Sta=294.7,304.1
XS Rating Curve= 0 ,0
Exp/Cntr(USF)=0,0
Exp/Cntr=0.3,0.1

Type RM Length L Ch R = 1 ,2176    ,237.4,230.4,220.6
XS GIS Cut Line= 5
 2199753.5091912755745.8738907432199734.38390011755715.391281812
2199572.60986094755550.1540366422199497.54181804755465.943183846
2199465.30346291755464.851097921
#Sta/Elev= 30
       0 1431.16    21.8    1429    47.6 1428.12    56.3 1427.45    79.2 1423.93
    90.6 1421.08    95.7 1420.07     102 1419.49   140.9 1419.29   173.4 1419.34
   187.8 1419.53   208.8 1418.94   227.8 1418.65     263 1419.42   293.7 1419.57
   305.1 1419.26   311.4  1418.4     316  1417.7   319.2 1418.37   322.1 1419.14
   324.9  1419.5   330.6 1419.89   344.7 1420.32     380 1420.91   382.1 1421.06
     389 1421.99   393.4 1422.83   397.6 1423.89   409.4 1427.46   412.3 1428.12
#Mann= 5 ,-1,0
       0     .06       0      30     .05       0  245.99     .06       0
   311.4    .045       0   319.2     .05       0
Bank Sta=311.4,319.2
XS Rating Curve= 0 ,0
Exp/Cntr(USF)=0,0
Exp/Cntr=0.3,0.1

Type RM Length L Ch R = 1 ,1946    ,51.2,54.8,57.8
XS GIS Cut Line= 4
2199791.96526906755492.3654863642199726.90164922755486.062198732
 2199725.3328955755484.9969955892199473.58645698755457.416815016
#Sta/Elev= 30
       0 1426.43     3.8 1425.93    11.8 1426.61    23.9 1426.36    27.9 1425.74
    31.9 1424.31      44 1419.01      48 1418.15      52 1418.43    61.3 1417.51
    66.9 1416.89    68.4 1416.94    71.41417.555    75.4 1418.59      79 1419.22
    84.5 1419.68    88.5 1419.75   111.7 1419.51   144.9 1419.74     161 1419.55
   177.2 1420.03   181.1 1419.96   189.1 1418.92   193.2 1418.95     206 1419.89
   213.2 1420.16   285.7 1420.22   297.8 1421.05   313.9 1423.47   320.5 1424.82
#Mann= 6 ,-1,0
       0     .06       0      60     .05       0    61.3    .045       0
    71.4     .05       0  157.26     .06       0  187.26     .05       0
#XS Ineff= 2 , 0
                          216.31         1422.18
Permanent Ineff=
       F       F
Bank Sta=61.3,71.4
XS Rating Curve= 0 ,0
Exp/Cntr(USF)=0,0
Exp/Cntr=0.3,0.1

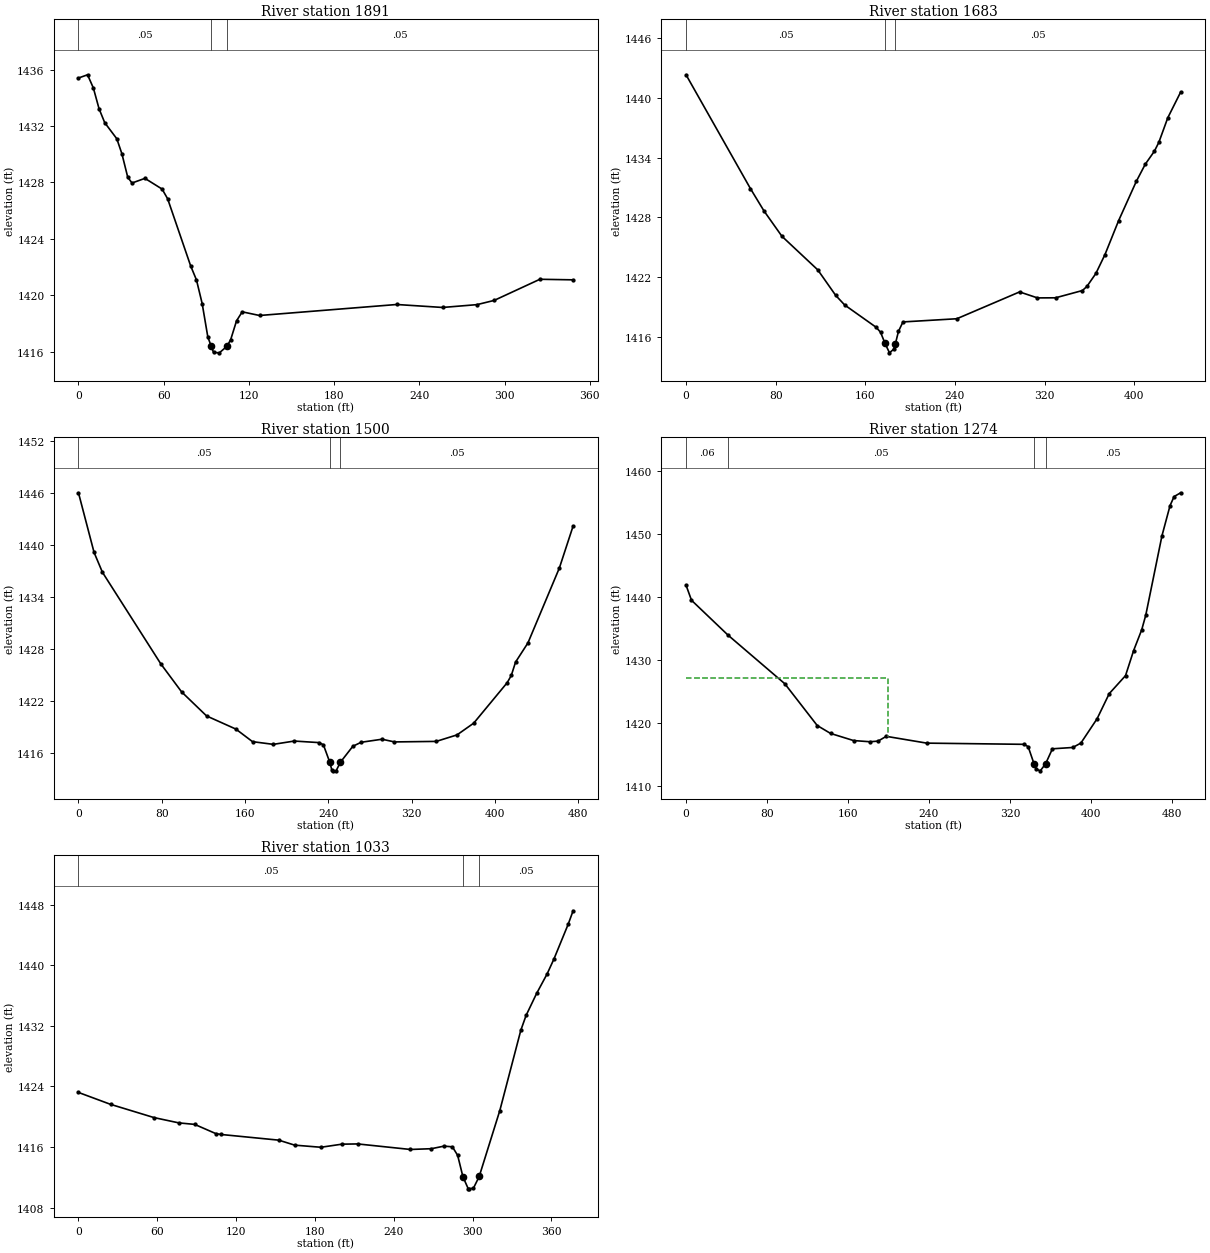
Type RM Length L Ch R = 1 ,1891    ,209.3,208.1,204.4
XS GIS Cut Line= 4
2199834.56853831755448.9560994712199737.93991264755436.708816564
2199736.75850552755436.8056532142199488.97511987755405.971843445
#Sta/Elev= 30
       0 1435.41     6.4 1435.64    10.5  1434.7    14.5 1433.23    18.5 1432.24
      27  1431.1    30.6 1430.03    34.7 1428.37    37.7 1427.96    46.8 1428.29
    58.9 1427.53    62.8 1426.84      79 1422.08    83.1 1421.08    87.1 1419.41
    91.1 1417.03    93.51416.376    95.1 1415.94    99.2 1415.91   104.61416.379
   107.2 1416.85   111.3 1418.18   115.3 1418.82   127.5 1418.56   224.1 1419.34
   256.4 1419.13   280.6 1419.33   292.7 1419.63   324.9 1421.13   348.3 1421.09
#Mann= 3 ,-1,0
       0     .05       0    93.5    .045       0   104.6     .05       0
Bank Sta=93.5,104.6
XS Rating Curve= 0 ,0
Exp/Cntr(USF)=0,0
Exp/Cntr=0.3,0.1

Type RM Length L Ch R = 1 ,1683    ,183.7,183,181.3
XS GIS Cut Line= 4
2199809.67496814 755261.05766783 2199715.2815419755264.926250872
2199505.60434101755271.8897003482199368.65650132 755281.17429965
#Sta/Elev= 30
       0  1442.3    57.5 1430.88    69.6 1428.64    85.6  1426.1   117.6 1422.73
   133.6 1420.17   141.6 1419.21   169.6 1416.98   173.6 1416.48   177.6 1415.36
   181.6 1414.41   185.6  1414.8  186.841415.309   189.6 1416.56   193.6 1417.51
   241.7 1417.83   297.7 1420.52   313.7 1419.92   329.8 1419.93   353.8 1420.66
   357.8 1421.07   365.8 1422.37   373.9 1424.26   386.1 1427.67   401.9 1431.61
   409.9 1433.33     418 1434.63     422 1435.52     430 1437.99   441.5 1440.57
#Mann= 3 ,0,0
       0     .05       0   177.6    .045       0  186.84     .05       0
Bank Sta=177.6,186.84
XS Rating Curve= 0 ,0
Exp/Cntr(USF)=0,0
Exp/Cntr=0.3,0.1

Type RM Length L Ch R = 1 ,1500    ,223.3,225.9,226.9
XS GIS Cut Line= 5
2199823.13587347755110.7754318712199768.30894452755107.680077231
2199588.75827991755098.085766909 2199570.4834031 755101.28387035
2199348.84898168755090.714757746
#Sta/Elev= 30
       0    1446      15 1439.13      23 1436.85    79.1  1426.3    99.1 1423.07
   123.1  1420.3   151.2 1418.79   167.2 1417.34   187.2 1417.03   207.3 1417.41
   231.3 1417.23   235.3 1416.98   241.4 1414.98   243.4 1414.09   244.8 1413.98
   247.5 1413.98   251.7 1414.98   263.6 1416.81   271.6 1417.27   291.6 1417.62
   303.6 1417.31   343.7 1417.37   363.7 1418.12   379.7 1419.47   411.8 1424.12
   415.8 1424.96   419.9  1426.5   431.8 1428.71     462 1437.34   475.2 1442.17
#Mann= 3 ,-1,0
       0     .05       0   241.4    .045       0   251.7     .05       0
Bank Sta=241.4,251.7
XS Rating Curve= 0 ,0
Exp/Cntr(USF)=0,0
Exp/Cntr=0.3,0.1

Type RM Length L Ch R = 1 ,1274    ,241.3,241,238.9
XS GIS Cut Line= 2
2199873.58593973754906.7436881612199385.69862757754878.040461474
#Sta/Elev= 30
       0  1441.9     5.4  1439.5    41.5 1433.96    97.6 1426.24   129.6 1419.61
   142.8 1418.35   165.5 1417.22   181.7 1417.03   189.7 1417.13   197.8 1417.89
   237.8 1416.81     334 1416.62     338 1416.25   343.91413.489     346 1412.67
     350 1412.41   355.21413.525     362 1415.91   382.1 1416.12   390.1 1416.82
   406.1 1420.68   418.1 1424.67   434.2 1427.53   442.2 1431.51   450.2 1434.81
   454.2 1437.13   470.2 1449.74   478.2 1454.54   482.2 1455.97   488.7 1456.57
#Mann= 4 ,-1,0
       0     .06       0    41.5     .05       0   343.9    .045       0
   355.2     .05       0
#XS Ineff= 2 , 0
          199.15 1427.15
Permanent Ineff=
       T       F
Bank Sta=343.9,355.2
XS Rating Curve= 0 ,0
Exp/Cntr(USF)=0,0
Exp/Cntr=0.3,0.1

Type RM Length L Ch R = 1 ,1033    ,236.2,235.9,234.5
XS GIS Cut Line= 2
2199792.51046101754637.1092730562199416.45554622754656.763711111
#Sta/Elev= 30
       0 1423.21    24.4 1421.64    57.5 1419.89    76.4 1419.19    88.5 1418.99
   104.5 1417.78   108.5 1417.66   152.5 1416.91   164.6 1416.25   184.6 1415.97
   200.6 1416.38   212.6 1416.41   252.7 1415.68   268.7 1415.78   278.3 1416.12
   284.7 1416.03   288.7  1414.9   292.7 1412.08   296.7 1410.51   297.3 1410.48
   300.7 1410.56   305.1 1412.11   320.8 1420.82   336.8 1431.43   340.8 1433.38
   348.8 1436.28   356.8 1438.86     362 1440.83   372.8  1445.4   376.6  1447.2
#Mann= 3 ,0,0
       0     .05       0   292.7    .045       0   305.1     .05       0
Bank Sta=292.7,305.1
XS Rating Curve= 0 ,0
Exp/Cntr(USF)=0,0
Exp/Cntr=0.3,0.1