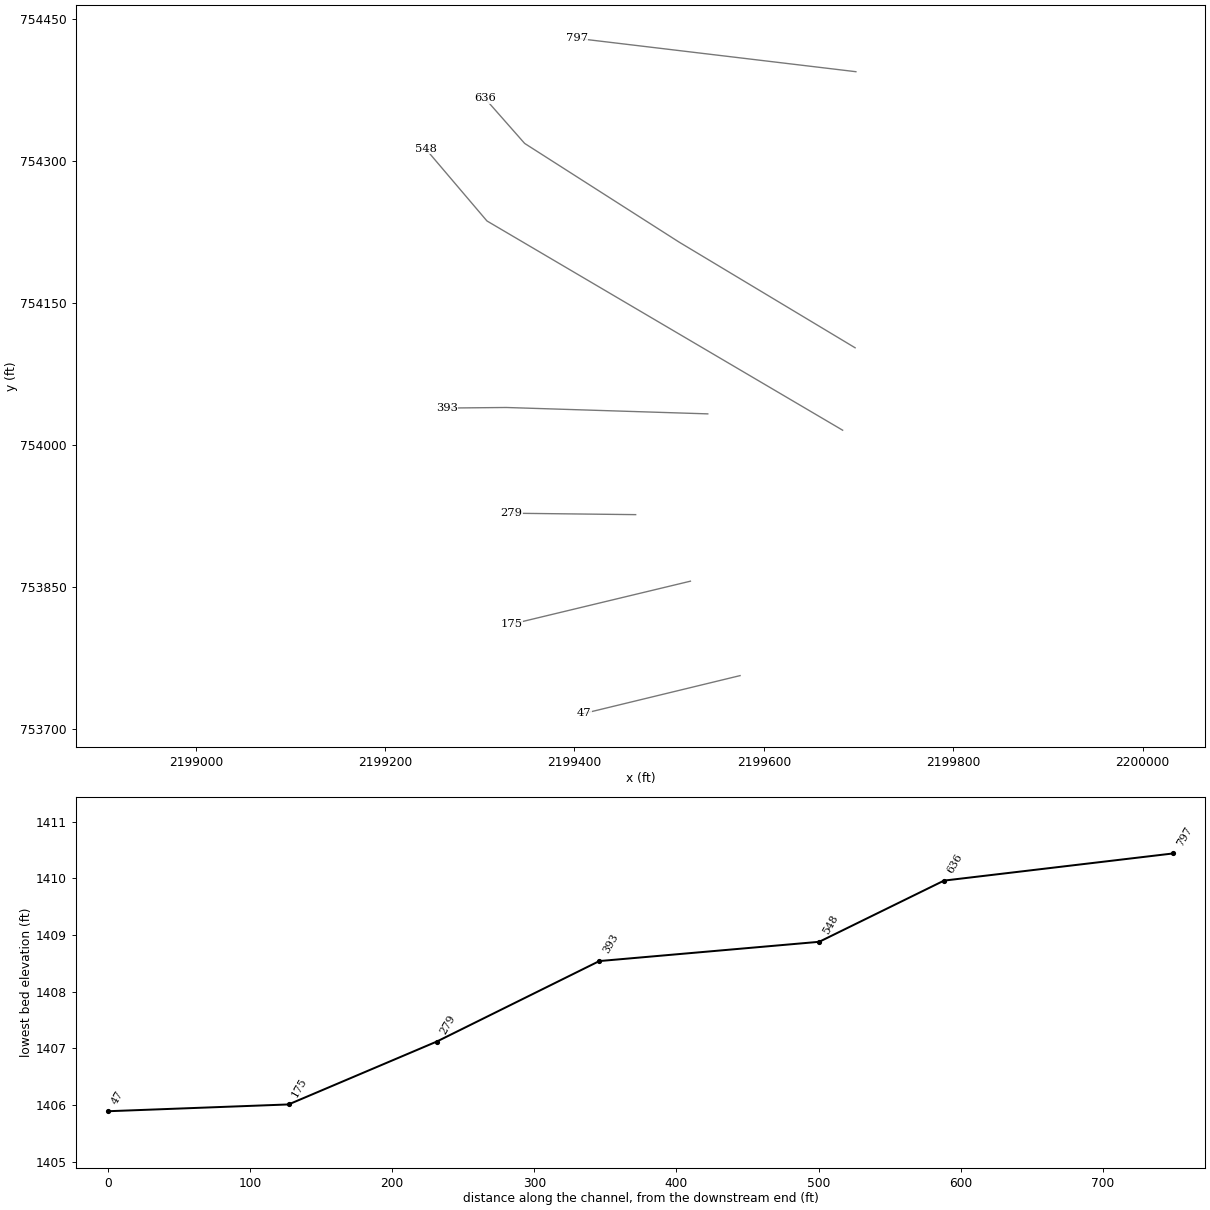
HEC-RAS study LIPECKSRN.prj: LIPECKSRN

--- LIPECKSRN.g01 (geometry) --- (continued)

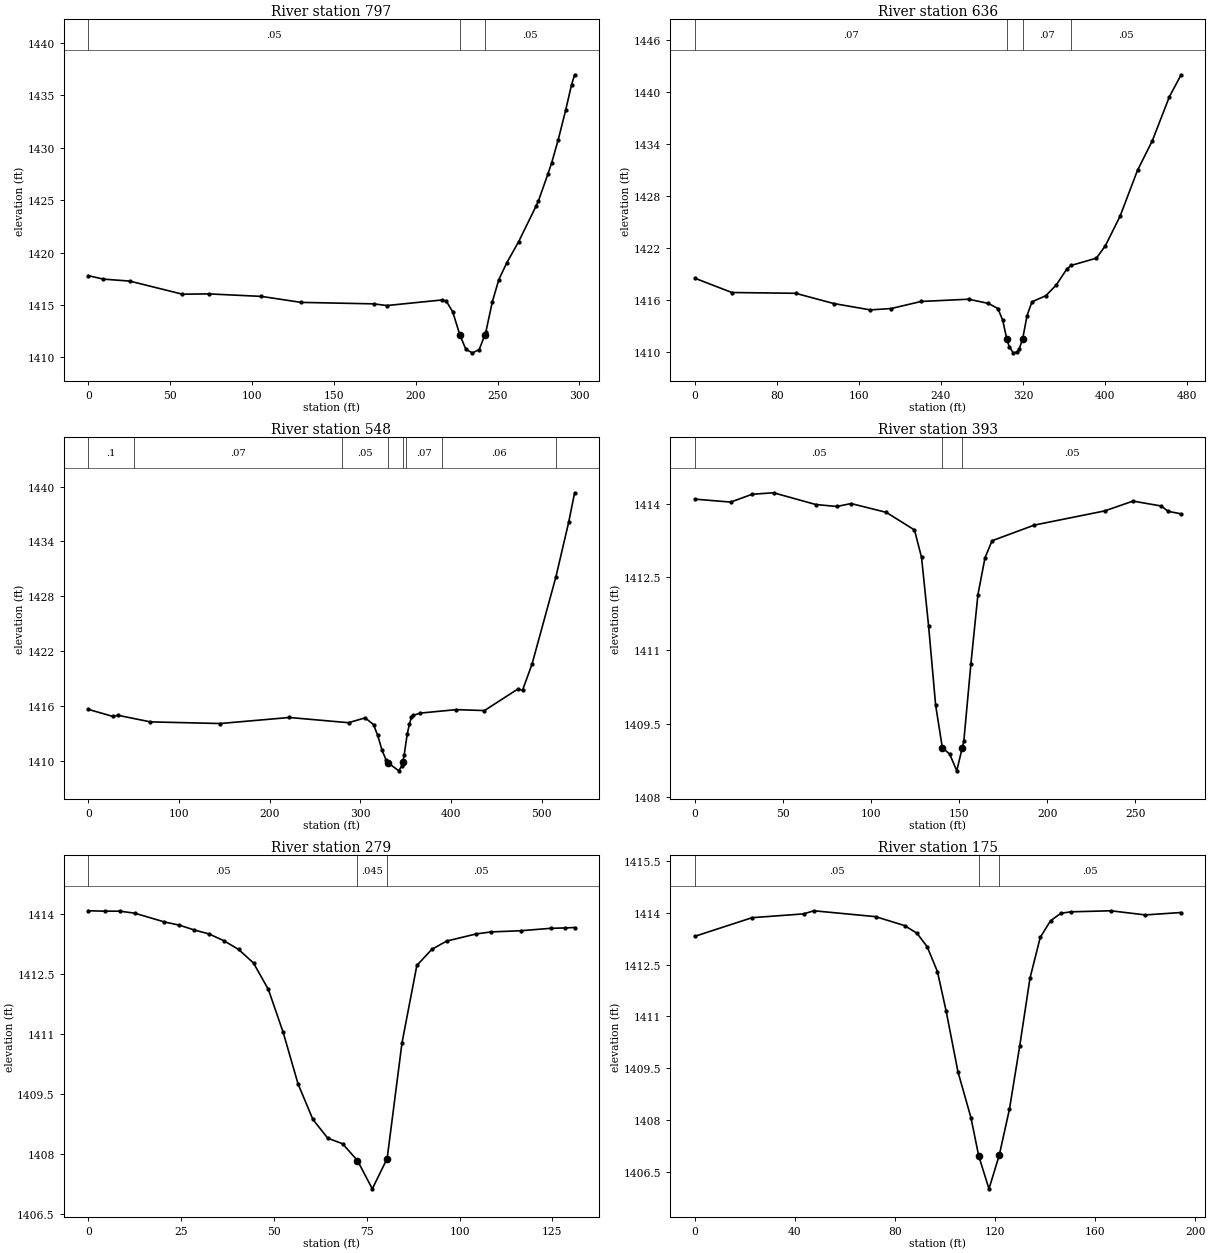
Type RM Length L Ch R = 1 ,797     ,166.5,161.4,155.1
XS GIS Cut Line= 2
2199697.25230191754394.1605856492199402.29960921754429.398681287
#Sta/Elev= 30
       0  1417.8     9.1 1417.47    25.3 1417.28    57.5 1416.03    73.6 1416.06
   105.8 1415.82     130 1415.25   174.3 1415.11   182.4 1414.95     216 1415.48
   218.6 1415.39   222.6 1414.36  226.991412.148   230.7 1410.76   234.7 1410.44
   238.8 1410.75   242.31412.171   242.8 1412.38   246.8 1415.29   250.8 1417.43
   255.6 1419.01   262.9 1421.04   273.6 1424.45     275 1424.93   280.8  1427.5
   283.1 1428.57   287.1 1430.77   291.6 1433.56   295.2 1435.99   297.1 1436.95
#Mann= 3 ,0,0
       0     .05       0  226.99    .045       0   242.3     .05       0
Bank Sta=226.99,242.3
XS Rating Curve= 0 ,0
Exp/Cntr(USF)=0,0
Exp/Cntr=0.3,0.1

Type RM Length L Ch R = 1 ,636     ,87.4,87.8,88.2
XS GIS Cut Line= 4
2199696.41956058754102.5546391182199510.51570229 754214.16074627
2199347.34501294754318.4247159792199305.22328886754366.251142476
#Sta/Elev= 30
       0 1418.55    36.2  1416.9    98.3 1416.81   135.6 1415.63   171.2  1414.9
   191.6 1415.06   220.7 1415.87     267 1416.13   286.1 1415.65   295.6 1415.06
   300.3  1413.7   304.2 1411.56   306.6 1410.68   310.5 1409.96   314.5 1410.06
   316.3 1410.39   319.71411.556     324 1414.25   328.8 1415.83   342.4 1416.54
   352.5 1417.77   362.6 1419.57   366.8 1420.01   391.6 1420.85   400.3 1422.27
   414.7 1425.68   431.7 1430.96   446.1 1434.35   462.8 1439.43   474.2 1441.95
#Mann= 4 ,-1,0
       0     .07       0   304.2    .045       0   319.7     .07       0
  366.83     .05       0
Bank Sta=304.2,319.7
XS Rating Curve= 0 ,0
Exp/Cntr(USF)=0,0
Exp/Cntr=0.3,0.1

Type RM Length L Ch R = 1 ,548     ,146.2,154.7,160.1
XS GIS Cut Line= 3
2199683.25610629754015.4810753812199307.53802761754236.517406029
2199242.58404073754312.933861186
#Sta/Elev= 30
       0 1415.61      27 1414.84    32.7 1414.96    68.5 1414.24   145.3 1414.06
   221.7 1414.72   286.9 1414.15   305.2 1414.68   314.5 1413.94   319.1 1412.75
   323.8 1411.16   328.4 1410.05   330.71409.743   342.4 1408.88   345.4  1409.4
  346.641409.795   348.3 1410.64   351.6 1412.88   354.1 1414.02   356.3 1414.75
   358.3 1414.95   365.8  1415.2   405.7 1415.58   436.8 1415.48   473.5 1417.83
   478.8 1417.71   489.3 1420.59   515.4 1430.05   529.6 1436.08   536.2 1439.32
#Mann= 8 ,-1,0
       0      .1       0      50     .07       0     280     .05       0
   330.7    .045       0  346.64     .05       0     350     .07       0
     390     .06       0  515.91     .05       0
Bank Sta=330.7,346.64
XS Rating Curve= 0 ,0
Exp/Cntr(USF)=0,0
Exp/Cntr=0.3,0.1

Type RM Length L Ch R = 1 ,393     ,113.1,114.3,113.9
XS GIS Cut Line= 3
2199540.80602507754032.7401427432199328.03310424754039.485309921
2199264.90456161754038.900517633
#Sta/Elev= 27
       0 1414.09    20.4 1414.03    32.6 1414.19    44.7 1414.22    68.7 1413.98
    80.7 1413.94    88.7    1414   108.7 1413.82   124.7 1413.46   128.7  1412.9
   132.7  1411.5   136.7 1409.88   140.51409.015   144.7 1408.88   148.7 1408.54
  151.811409.013   152.7 1409.15   156.7 1410.72   160.7 1412.14   164.7 1412.89
   168.7 1413.24   192.7 1413.56   232.7 1413.85   248.7 1414.05   264.7 1413.95
   268.7 1413.84     276 1413.79
#Mann= 3 ,0,0
       0     .05       0   140.5    .045       0  151.81     .05       0
Bank Sta=140.5,151.81
XS Rating Curve= 0 ,0
Exp/Cntr(USF)=0,0
Exp/Cntr=0.3,0.1

Type RM Length L Ch R = 1 ,279     ,101.8,104.3,106.2
XS GIS Cut Line= 2
2199464.62910322753926.3077116622199333.62158544753927.799688313
#Sta/Elev= 30
       0 1414.09     4.5 1414.08     8.5 1414.08    12.5 1414.03    20.5 1413.81
    24.5 1413.73    28.5 1413.61    32.5 1413.51    36.5 1413.34    40.5 1413.12
    44.5 1412.78    48.5 1412.12    52.5 1411.04    56.5 1409.75    60.5 1408.86
    64.5 1408.39    68.5 1408.25    72.5 1407.83    76.5 1407.12    80.5 1407.88
    84.5 1410.78    88.5 1412.72    92.5 1413.12    96.5 1413.33   104.5 1413.51
   108.5 1413.56   116.5 1413.59   124.5 1413.65   128.5 1413.66     131 1413.67
#Mann= 3 ,-1,0
       0     .05       0    72.5    .045       0    80.5     .05       0
Bank Sta=72.5,80.5
XS Rating Curve= 0 ,0
Exp/Cntr(USF)=0,0
Exp/Cntr=0.3,0.1

Type RM Length L Ch R = 1 ,175     ,127.1,127.1,127.1
XS GIS Cut Line= 2
2199522.47903169753856.0259439752199333.42137221753810.605931865
#Sta/Elev= 25
       0 1413.32    22.9 1413.86    43.5 1413.97    47.6 1414.06    72.3 1413.89
    83.9 1413.63    88.8 1413.41    92.9 1413.02      97  1412.3   100.5 1411.15
   105.2  1409.4   110.4 1408.07   113.51406.963   117.6 1406.01   121.7 1406.98
   125.8 1408.32   129.9 1410.15     134 1412.11   138.1 1413.29   142.2 1413.77
   146.4 1413.99   150.5 1414.03   166.3 1414.06   180.1 1413.94   194.4 1414.01
#Mann= 3 ,-1,0
       0     .05       0   113.5    .045       0   121.7     .05       0
Bank Sta=113.5,121.7
XS Rating Curve= 0 ,0
Exp/Cntr(USF)=0,0
Exp/Cntr=0.3,0.1

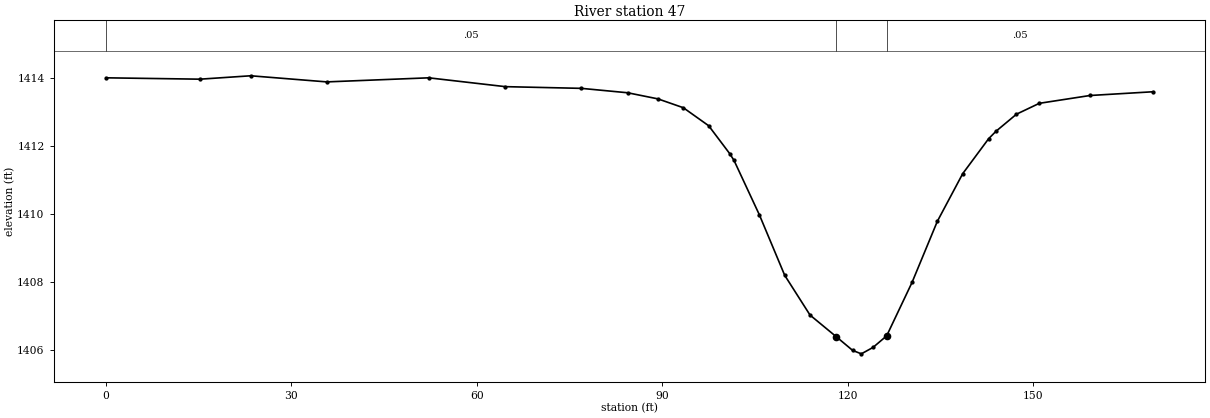
Type RM Length L Ch R = 1 ,47      ,,,
XS GIS Cut Line= 2
2199574.91766891753756.2802889622199410.31322148753716.392261135
#Sta/Elev= 30
       0 1414.01    15.2 1413.97    23.4 1414.07    35.7 1413.89    52.2 1414.01
    64.6 1413.75    76.9  1413.7    84.4 1413.57    89.3 1413.39    93.4 1413.13
    97.5  1412.6   100.9 1411.78   101.6 1411.58   105.7 1409.98   109.8  1408.2
   113.9 1407.03   118.1  1406.4   120.8 1405.99   122.2 1405.89   124.1 1406.08
   126.3 1406.42   130.4 1407.99   134.5 1409.79   138.6 1411.19   142.8 1412.22
     144 1412.44   147.3 1412.94     151 1413.26   159.2 1413.49   169.4  1413.6
#Mann= 3 ,-1,0
       0     .05       0   118.1    .045       0   126.3     .05       0
Bank Sta=118.1,126.3
XS Rating Curve= 0 ,0
Exp/Cntr(USF)=0,0
Exp/Cntr=0.3,0.1
LCMann Table=0

Chan Stop Cuts=-1
Use User Specified Reach Order=0
Composite Channel Slope=5